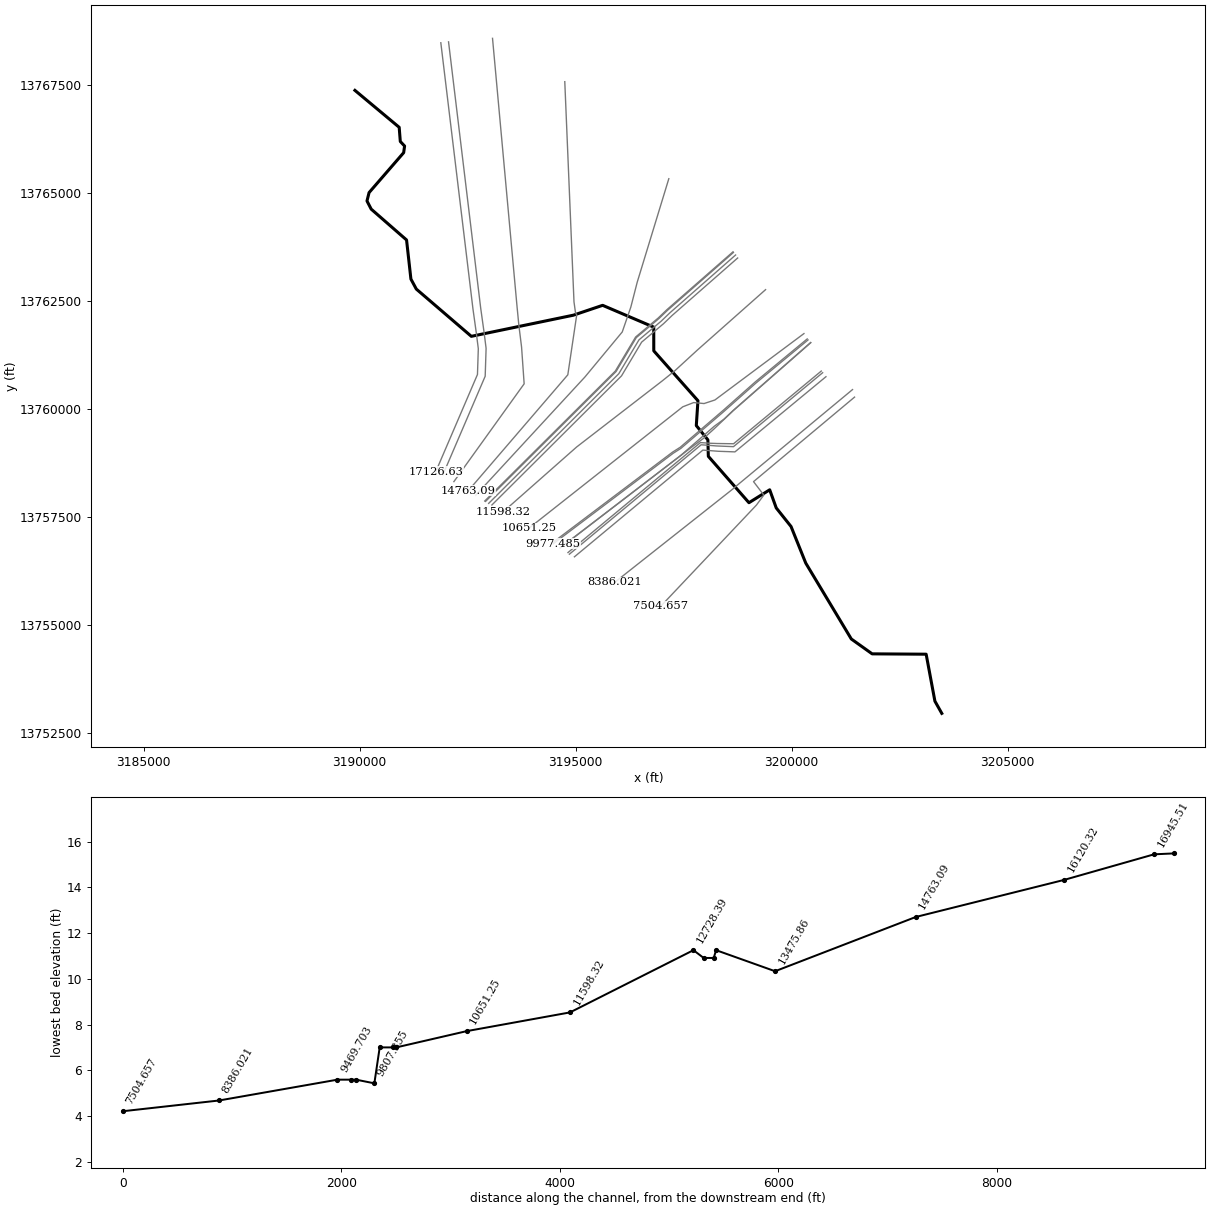
--- A111_00_00.prj (project) ---

Proj Title=A111-00-00
Current Plan=p01
Default Exp/Contr=.3,.1
English Units
Geom File=g01
Geom File=g02
Flow File=f01
Flow File=f02
Plan File=p01
Plan File=p02
Y Axis Title=Elevation
X Axis Title(PF)=Main Channel Distance
X Axis Title(XS)=Station
BEGIN DESCRIPTION:
Clear Creek Basin
Clear Creek Tributary 10.08
A111-00-00
Flood Hazard Model
10, 2, 1 & 0.2% Events
Filename: A111_00_00.prj
Prepared by: Perry Vaught	Date: 4-27-04
Reviewed by: __________	Date:
Status: (FINAL)
END DESCRIPTION:
DSS Export Rating Curves= 0
DSS Export Rating Curve Sorted= 0
DSS Export Volume Flow Curves= 0
DXF OffsetX= 0
DXF OffsetY= 0
DXF ScaleX= 1
DXF ScaleY= 10

--- A111_00_00.p01 (plan) ---

Plan Title=FEMA Effective June 2007
Version=Version 3.0.1  Mar 2001
Short Identifier=FEMAeff0607
Geom File=g01
Flow File=f01
Subcritical Flow
K Sum by GR= 0
Std Step Tol= 0.01
Critical Tol= 0.01
Num of Std Step Trials= 20
Max Error Tol= 0.3
Flow Tol Ratio= 0.001
Split Flow NTrial= 30
Split Flow Tol= 0.02
Split Flow Ratio= 0.02
Log Output Level= 0
Friction Slope Method= 0
Unsteady Friction Slope Method= 2
Secant Critical Depth
Global Vel Dist= 0 , 0 , 0
Global Log Level= 0
CheckData=True
Encroach Param=-1 ,0,0, 2
Computation Interval=1HOUR
Output Interval=1HOUR
Run HTab= 0
Run UNet= 0
Run PostProcess= 0
UNET Theta= 1
UNET ZTol= 0.02
UNET ZSATol= 0.1
UNET MxIter= 20
UNET MaxInSteps= 20
UNET DtIC= 0
UNET DtMin= 0
UNET MaxCRTS= 20
UNET WFStab= 2
UNET SFStab= 1
UNET WFX= 1
UNET SFX= 1
UNET Convert EG Bridges=-1
UNET Use Existing IB Tables=-1
Instantaneous Interval=1HOUR
Write IC File= 0
Write Velocity= 0
Write Detailed= 0

--- A111_00_00.p02 (plan) ---

Plan Title=Floodway
Version=Version 3.0.1  Mar 2001
Short Identifier=Floodway0607
Geom File=g02
Flow File=f02
Subcritical Flow
K Sum by GR= 0
Std Step Tol= 0.01
Critical Tol= 0.01
Num of Std Step Trials= 20
Max Error Tol= 0.3
Flow Tol Ratio= 0.001
Split Flow NTrial= 30
Split Flow Tol= 0.02
Split Flow Ratio= 0.02
Log Output Level= 0
Friction Slope Method= 0
Unsteady Friction Slope Method= 2
Secant Critical Depth
Global Vel Dist= 0 , 0 , 0
Global Log Level= 0
CheckData=True
Encroach Param=-1 ,0,0, 2
Encroach River=A111-00-00
Encroach Reach=A111-00-00_0020
Encroach Node=17126.63
       1 6775.05 6898.02
Encroach Node=16945.51
       1 4908.23 5050.48
Encroach Node=16120.32
       1 4953.27 5046.73
Encroach Node=14763.09
       1 4968.32 5068.03
Encroach Node=13475.86
       1 4925.31 5079.05
Encroach Node=12935.82
       1 4922.73 5030.24
Encroach Node=12913.91
       1 4922.73 5030.24
Encroach Node=12862
       1 4922.73 5030.24
Encroach Node=12822.08
       1 4922.73 5030.24
Encroach Node=12728.39
       1 4922.73 5080.69
Encroach Node=11598.32
       1  4933.8 5036.28
Encroach Node=10651.25
       1 4964.94 5036.68
Encroach Node=10007.5
       1 4933.02 5046.98
Encroach Node=9977.485
       1 4923.02 5036.98
Encroach Node=9916
       1 4923.02 5036.98
Encroach Node=9856.212
       1 4923.02 5036.98
Encroach Node=9807.355
       1 4933.21 5051.91
Encroach Node=9805
       1 4933.21 5051.91
Encroach Node=9639.737
       1 4933.21 5051.91
Encroach Node=9614
       1 4933.21 5051.91
Encroach Node=9589.726
       1 4933.21 5051.91
Encroach Node=9469.703
       1 4966.76 5033.24
Encroach Node=8386.021
       1 4966.33 5033.67
Encroach Node=7504.657
       1 4966.83 5033.17
Encroach Node=7416.087
       1  4969.2  5030.8
Encroach Node=7381.155
       1  4969.2  5030.8
Encroach Node=7379
       1  4969.2  5030.8
Encroach Node=7377.046
       1  4969.2  5030.8
Encroach Node=7308.124
       1  4969.2  5030.8
Encroach Node=7186.633
       1 4949.78 5028.41
Encroach Node=5857.266
       1 4961.06 5038.94
Encroach Node=4720.374
       1 4956.64 5029.16
Encroach Node=4690.362
       1    4956    5049
Encroach Node=4669
       1    4956    5049
Encroach Node=4650.352
       1    4956    5049
Encroach Node=4530.347
       1    4954    5087
Encroach Node=3840.003
       1 4859.19 5190.44
Encroach Node=3254.865
       1 4827.34 5101.35
Encroach Node=2739.518
       1 4969.42 5059.64
Encroach Node=2719.165
       1 4834.42 5059.64
Encroach Node=2706
       1 4969.42 5059.64
Encroach Node=2688.931
       1 4839.42 5059.64
Encroach Node=2608.866
       1 4930.84 5106.33
Encroach Node=2334.135
       1  4935.7 5082.04
Encroach Node=2312.034
       1  4935.7 5082.04
Encroach Node=2158
       1    4957    5039
Encroach Node=2044.285
       1    4850    5044
Encroach Node=1951.766
       1    4900    5044
Computation Interval=1HOUR
Output Interval=1HOUR
Run HTab= 0
Run UNet= 0
Run PostProcess= 0
UNET Theta= 1
UNET ZTol= 0.02
UNET ZSATol= 0.1
UNET MxIter= 20
UNET MaxInSteps= 20
UNET DtIC= 0
UNET DtMin= 0
UNET MaxCRTS= 20
UNET WFStab= 2
UNET SFStab= 1
UNET WFX= 1
UNET SFX= 1
UNET Convert EG Bridges=-1
UNET Use Existing IB Tables=-1
Instantaneous Interval=1HOUR
Write IC File= 0
IC Time=0
Write Velocity= 0
Write Detailed= 0

--- A111_00_00.f01 (steady flow) ---

Flow Title=FEMA Effective June 2007
Version=Version 3.0.1  Mar 2001
Number of Profiles= 4
Profile Names=10PCT_10yr, 2PCT_50yr, 1PCT_100yr, 0.2PCT_500yr
River Rch & RM=A111-00-00,A111-00-00_0020      ,17126.63
     339     522     619     906
River Rch & RM=A111-00-00,A111-00-00_0020      ,16945.51
     339     522     619     906
River Rch & RM=A111-00-00,A111-00-00_0020      ,16120.32
     410     632     749    1096
River Rch & RM=A111-00-00,A111-00-00_0020      ,14763.09
     492     757     897    1314
River Rch & RM=A111-00-00,A111-00-00_0020      ,13475.86
     531     817     968    1418
River Rch & RM=A111-00-00,A111-00-00_0020      ,12935.82
     539     830     984    1441
River Rch & RM=A111-00-00,A111-00-00_0020      ,12822.08
     640     986    1169    1711
River Rch & RM=A111-00-00,A111-00-00_0020      ,11598.32
     732    1127    1335    1955
River Rch & RM=A111-00-00,A111-00-00_0020      ,10651.25
     801    1234    1462    2140
River Rch & RM=A111-00-00,A111-00-00_0020      ,10007.5
     804    1239    1468    2149
River Rch & RM=A111-00-00,A111-00-00_0020      ,9977.485
     819    1262    1495    2189
River Rch & RM=A111-00-00,A111-00-00_0020      ,9469.703
     852    1312    1554    2276
River Rch & RM=A111-00-00,A111-00-00_0020      ,8386.021
     890    1370    1623    2377
River Rch & RM=A111-00-00,A111-00-00_0020      ,7186.633
     933    1437    1703    2494
River Rch & RM=A111-00-00,A111-00-00_0020      ,5857.266
     972    1498    1774    2598
River Rch & RM=A111-00-00,A111-00-00_0020      ,4720.374
    1004    1546    1831    2682
River Rch & RM=A111-00-00,A111-00-00_0020      ,3840.003
    1049    1616    1914    2803
River Rch & RM=A111-00-00,A111-00-00_0020      ,2608.866
    1074    1655    1960    2870
Boundary for River Rch & Prof#=A111-00-00,A111-00-00_0020      , 1
Up Type= 0
Dn Type= 3
Dn Slope=.002
Boundary for River Rch & Prof#=A111-00-00,A111-00-00_0020      , 2
Up Type= 0
Dn Type= 3
Dn Slope=.002
Boundary for River Rch & Prof#=A111-00-00,A111-00-00_0020      , 3
Up Type= 0
Dn Type= 3
Dn Slope=.002
Boundary for River Rch & Prof#=A111-00-00,A111-00-00_0020      , 4
Up Type= 0
Dn Type= 3
Dn Slope=.002
DSS Import GetInterval= 0
DSS Import GetPeak= 0
DSS Import FillOption= 0

--- A111_00_00.f02 (steady flow) ---

Flow Title=Floodway
Program Version=3.11
Number of Profiles= 2
Profile Names=1PCT_100yr, 1PCTFloodway_100yrFW
River Rch & RM=A111-00-00,A111-00-00_0020      ,17126.63
     619     619
River Rch & RM=A111-00-00,A111-00-00_0020      ,16945.51
     619     619
River Rch & RM=A111-00-00,A111-00-00_0020      ,16120.32
     749     749
River Rch & RM=A111-00-00,A111-00-00_0020      ,14763.09
     897     897
River Rch & RM=A111-00-00,A111-00-00_0020      ,13475.86
     968     968
River Rch & RM=A111-00-00,A111-00-00_0020      ,12935.82
     984     984
River Rch & RM=A111-00-00,A111-00-00_0020      ,12822.08
    1169    1169
River Rch & RM=A111-00-00,A111-00-00_0020      ,11598.32
    1335    1335
River Rch & RM=A111-00-00,A111-00-00_0020      ,10651.25
    1462    1462
River Rch & RM=A111-00-00,A111-00-00_0020      ,10007.5
    1468    1468
River Rch & RM=A111-00-00,A111-00-00_0020      ,9977.485
    1495    1495
River Rch & RM=A111-00-00,A111-00-00_0020      ,9469.703
    1554    1554
River Rch & RM=A111-00-00,A111-00-00_0020      ,8386.021
    1623    1623
River Rch & RM=A111-00-00,A111-00-00_0020      ,7186.633
    1703    1703
River Rch & RM=A111-00-00,A111-00-00_0020      ,5857.266
    1774    1774
River Rch & RM=A111-00-00,A111-00-00_0020      ,4720.374
    1831    1831
River Rch & RM=A111-00-00,A111-00-00_0020      ,3840.003
    1914    1914
River Rch & RM=A111-00-00,A111-00-00_0020      ,2608.866
    1960    1960
Boundary for River Rch & Prof#=A111-00-00,A111-00-00_0020      , 1
Up Type= 0
Dn Type= 3
Dn Slope=0.002
Boundary for River Rch & Prof#=A111-00-00,A111-00-00_0020      , 2
Up Type= 0
Dn Type= 3
Dn Slope=0.002
DSS Import GetInterval= 0
DSS Import GetPeak= 0
DSS Import FillOption= 0

--- A111_00_00.g01 (geometry) ---

Geom Title=A111-00-00 June 2007
Version=Version 3.0.1  Mar 2001

River Reach=A111-00-00,A111-00-00_0020
Reach XY= 30
     3189891.634    13767372.474     3190916.346    13766517.143
      3190942.25    13766188.999       3191041.5    13766083.999
        3191020.       13765930.      3190219.25       13765006.
      3190170.75    13764811.999       3190268.5       13764623.
        3191087.    13763908.999      3191187.75    13763003.999
        3191313.    13762771.999       3192586.5       13761678.
      3194950.75       13762168.      3195626.75    13762395.999
      3196809.75       13761891.       3196810.5       13761342.
        3197833.    13760187.999        3197795.    13759611.999
        3198063.    13759281.001       3198073.5    13758899.999
      3199013.75       13757826.      3199494.25       13758125.
      3199645.75    13757705.001       3199988.5       13757275.
        3200329.    13756427.999      3201383.75       13754671.
      3201866.25       13754327.      3203116.25       13754319.
        3203319.    13753232.001      3203478.25       13752949.

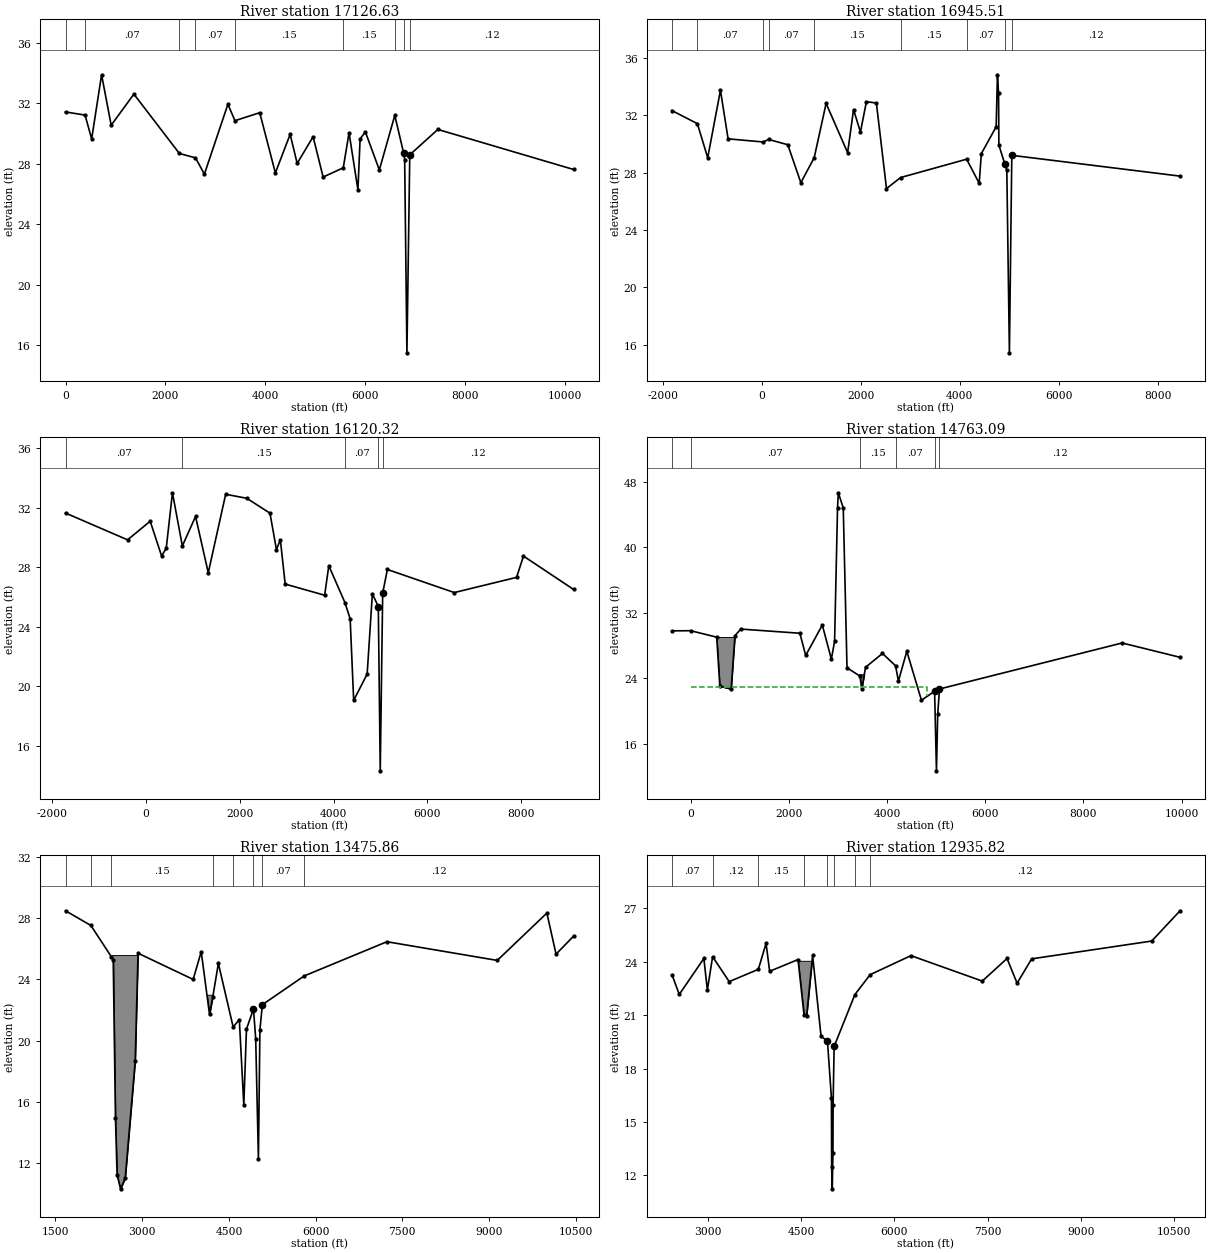
Type RM Length L Ch R = 1 ,17126.63,180.06,181.12,180.64
XS GIS Cut Line= 6
     3191880.331    13768474.686     3192623.995    13762315.207
     3192702.547    13761751.291      3192748.15    13761391.671
     3192728.709    13760794.547     3191764.314    13758546.583
#Sta/Elev= 30
       0   31.43  391.83   31.22  524.09   29.64  722.78   33.89  915.19   30.55
 1370.35   32.61 2281.53   28.68 2604.58   28.39 2782.92   27.31 3253.86   31.94
  3395.4   30.85 3891.65   31.38 4204.89   27.39 4501.21   29.95 4641.87   28.02
 4961.23   29.79 5161.73   27.12 5565.53   27.73 5681.38   30.05 5859.37   26.27
 5902.86   29.65 6009.17    30.1 6288.46   27.59 6597.73    31.2 6775.05   28.71
 6795.62   28.27 6840.92   15.48 6898.02   28.59 7461.05   30.2710179.62   27.62
#Mann= 9 ,-1 , 0
       0     .12       0  391.83     .07       0 2281.53     .15       0
 2604.58     .07       0  3395.4     .15       0 5565.53     .15       0
 6597.73     .07       0 6775.05    .035       0 6898.02     .12       0
Bank Sta=6775.05,6898.02
XS Rating Curve= 0
Exp/Cntr=.3,.1

Type RM Length L Ch R = 1 ,16945.51,830.65,825.19,823.43
XS GIS Cut Line= 6
     3192059.033    13768496.262       3192802.5    13762338.414
     3192881.135    13761773.903     3192928.535    13761400.556
     3192907.509     13760754.77     3191929.734    13758475.617
#Sta/Elev= 30
-1822.64   32.34-1308.89   31.43-1099.97   29.05 -842.22   33.76 -687.57   30.37
   26.87   30.15  129.63   30.33   519.7   29.96  783.84   27.31 1054.38   29.06
 1294.74   32.84 1729.87   29.41  1849.9   32.41 1988.96   30.84 2109.23   32.96
 2311.62   32.87 2516.13    26.9 2801.14   27.67  4136.9   28.95 4390.91   27.27
 4434.48   29.34 4733.66   31.21 4760.04   34.84 4782.83   33.54 4788.99   29.94
 4908.23   28.62 4949.52   28.17  5001.9   15.44 5050.48   29.22 8452.42   27.77
#Mann= 9 ,-1 , 0
-1822.64     .12       0-1308.89     .07       0   26.87     .15       0
  129.63     .07       0 1054.38     .15       0 2801.14     .15       0
  4136.9     .07       0 4908.23    .035       0 5050.48     .12       0
Bank Sta=4908.23,5050.48
XS Rating Curve= 0
Exp/Cntr=.3,.1

Type RM Length L Ch R = 1 ,16120.32,1333.76,1357.23,1318.28
XS GIS Cut Line= 6
      3193077.26    13768577.074     3193642.941    13762386.901
     3193686.248    13761940.943     3193749.902    13761427.783
     3193809.491    13760578.641     3192182.751    13758314.024
#Sta/Elev= 30
-1708.85   31.63 -386.96   29.83   95.03   31.08  337.44   28.75  435.99   29.25
  568.87   32.99  779.92   29.42 1061.08    31.4 1331.63   27.62 1702.25   32.89
 2151.98   32.62 2646.17   31.62 2783.77   29.18  2867.3   29.83 2970.05   26.86
 3810.63   26.11 3898.98   28.09 4242.55   25.62    4354   24.53 4428.82   19.05
  4716.1   20.82 4827.01   26.21 4953.27   25.35 4994.66   14.32 5046.73   26.25
 5146.72   27.84 6571.69   26.29 7898.24   27.31 8045.56   28.74 9111.88    26.5
#Mann= 5 ,-1 , 0
-1708.85     .07       0  779.92     .15       0 4242.55     .07       0
 4953.27    .035       0 5046.73     .12       0
#XS Ineff= 2 , 0
       0    4830    26.1               0
Permanent Ineff=
       F       F
Bank Sta=4953.27,5046.73
XS Rating Curve= 0
Exp/Cntr=.3,.1

Type RM Length L Ch R = 1 ,14763.09,1388.49,1287.23,1156.97
XS GIS Cut Line= 6
     3194750.178    13767573.971      3194963.29    13762476.986
     3194997.409    13762229.808     3195026.515     13762173.54
     3194820.302    13760786.797     3192519.242    13758106.952
#Sta/Elev= 30
 -381.57    29.8    -.15   29.82  529.61   29.03  593.24   23.05  823.86   22.69
  901.07   29.21 1018.97   30.02 2223.28   29.51 2343.04    26.8 2680.74   30.51
 2865.43   26.35 2930.92   28.53 2990.98   44.82 3007.65   46.67 3107.57   44.82
 3184.12   25.29 3447.63   24.27 3483.65   22.68 3561.47   25.35 3906.51   27.04
 4172.07   25.54  4231.8   23.67 4402.11   27.31 4700.57   21.32 4968.32   22.43
 5006.08    12.7 5031.68   19.63 5068.03    22.7 8788.31   28.32  9967.6   26.57
#Mann= 6 ,-1 , 0
 -381.57     .15       0    -.15     .07       0 3447.63     .15       0
 4172.07     .07       0 4968.32    .035       0 5068.03     .12       0
#XS Ineff= 2 , 0
       0    4815   22.96               0
Permanent Ineff=
       F       F
#Block Obstruct= 2 ,-1
  519.67  985.65   29.05    3420    3560    24.5
Bank Sta=4968.32,5068.03
XS Rating Curve= 0
Exp/Cntr=.3,.1

Type RM Length L Ch R = 1 ,13475.86,648.88,540.04,358.65
XS GIS Cut Line= 6
     3197158.776    13765327.513     3196427.303    13762931.762
     3196279.625    13762356.908     3196080.581    13761779.197
     3195216.583    13760737.055      3192690.68     13758000.74
#Sta/Elev= 30
 1674.04   28.48  2113.4   27.52 2464.89   25.49 2499.59   25.28 2537.77   14.95
 2566.05   11.24 2625.77   10.33 2707.18   11.03 2879.73   18.68 2928.69   25.71
 3881.87      24 4021.54   25.81 4165.21   21.71 4222.33   22.88 4318.02   25.04
 4573.82   20.89 4680.22   21.38 4758.08   15.81 4804.04   20.76 4925.31   22.07
 4963.68   20.13 5010.72   12.28 5036.32    20.7 5079.05   22.35 5804.03   24.23
 7233.44   26.46 9141.59   25.2410000.04   28.3310158.56   25.6510461.26   26.82
#Mann= 8 ,-1 , 0
 1674.04     .15       0  2113.4     .07       0 2464.89     .15       0
 4222.33     .07       0 4573.82     .12       0 4925.31    .035       0
 5079.05     .07       0 5804.03     .12       0
#Block Obstruct= 2 ,-1
 2482.81 2935.42   25.59    4120    4250      23
Bank Sta=4925.31,5079.05
XS Rating Curve= 0
Exp/Cntr=.3,.1

Type RM Length L Ch R = 1 ,12935.82,20.02,21.91,20.8
XS GIS Cut Line= 6
     3198643.683     13763633.66     3197111.399    13762292.022
     3196917.045    13762105.409     3196390.001    13761661.595
     3195920.999    13760874.529     3192897.795    13757865.908
#Sta/Elev= 30
 2420.24   23.28 2537.57   22.17 2933.52   24.19 2989.81   22.42 3074.38   24.29
 3341.42   22.89 3810.28   23.58 3934.75   25.04 3991.93   23.47 4449.07   24.13
 4546.19      21    4587   20.95 4683.76   24.36 4819.79   19.81 4922.73   19.56
 4986.79   16.33 4990.08   12.49 4999.75   11.25 5011.29   13.27 5013.21   15.98
 5030.24   19.25 5363.86   22.16 5609.16   23.28 6266.31   24.35 7414.57   22.92
 7812.89   24.19 7974.88    22.8 8209.33   24.1710141.91   25.1710596.97   26.87
#Mann= 8 ,-1 , 0
 2420.24     .07       0 3074.38     .12       0 3810.28     .15       0
 4546.19     .07       0 4922.73    .035       0 5030.24     .12       0
 5363.86     .07       0 5609.16     .12       0
#Block Obstruct= 1 ,-1
 4433.31 4673.57   24.06
Bank Sta=4922.73,5030.24
XS Rating Curve= 0
Exp/Cntr=.5,.3

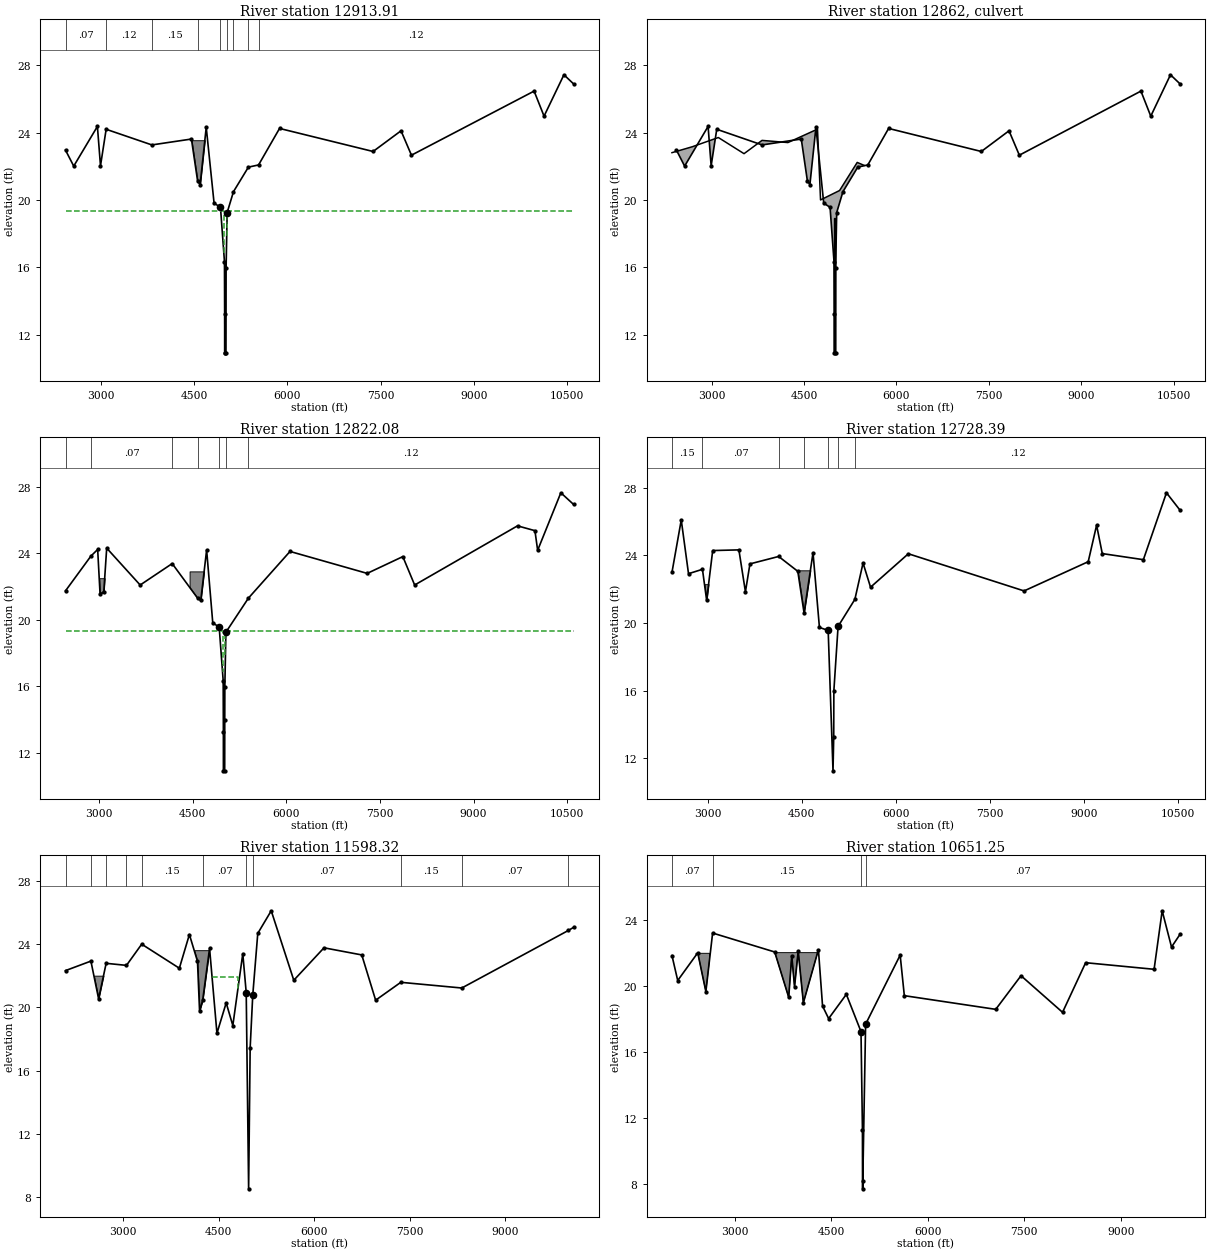
Type RM Length L Ch R = 1 ,12913.91,80.06,91.83,93.7
XS GIS Cut Line= 6
     3198654.827     13763619.73     3197124.949    13762277.306
     3196930.377    13762090.483     3196405.437    13761648.429
     3195936.893    13760862.132      3192915.59    13757856.201
#Sta/Elev= 30
  2430.9   22.96 2563.23   22.01 2943.85   24.37 2993.54   22.03 3084.41    24.2
  3819.6   23.27 4455.57   23.62  4554.8   21.13 4595.54   20.91 4693.63   24.32
 4819.79   19.81 4922.73   19.56 4986.79   16.33 4989.77   13.23    4990   10.92
 4999.79   10.91 5010.95   10.91 5013.21   15.98 5030.24   19.25 5131.48   20.49
 5371.68   21.95 5535.06   22.08  5872.5   24.25 7376.46   22.88 7825.79   24.11
 7993.25   22.66 9965.69   26.4710125.44   24.9810444.98   27.4410599.75    26.9
#Mann= 9 ,-1 , 0
  2430.9     .07       0 3084.41     .12       0  3819.6     .15       0
  4554.8     .07       0 4922.73    .015       0 5030.24     .07       0
 5131.48     .12       0 5371.68     .07       0 5535.06     .12       0
#XS Ineff= 2 , 0
       0    4976   19.35    5023       0   19.35
Permanent Ineff=
       F       F
#Block Obstruct= 1 ,-1
 4450.72  4687.6   23.55
Bank Sta=4922.73,5030.24
XS Rating Curve= 0
Exp/Cntr=.5,.3

Type RM Length L Ch R = 2 ,12862   ,,,
BEGIN DESCRIPTION:
MEDICAL CENTER BLVD
END DESCRIPTION:
Bridge Culvert--1,0,-1,-1, 0
Deck Dist Width WeirC Skew NumUp NumDn MinLoCord MaxHiCord MaxSubmerge Is_Ogee
14,69,2.6,0, 11, 11, , , .95, 0, 0,0,,
    2358    2686    3110    3527    3819    4239    4719    4768    5077    5363
    5472
   22.81   23.16   23.71   22.75   23.54   23.41   24.21      20   20.56   22.23
   22.06
                                                                                
        
    2358    2686    3110    3527    3819    4239    4719    4768    5077    5363
    5472
   22.81   23.16   23.71   22.75   23.54   23.41   24.21      20   20.56   22.23
   22.06
                                                                                
        
Culvert=2,8,8.7,69,.012,.5,1,10,1,10.93,4995.15,10.89,4995.15,Culvert #1  , 0 ,14
Culvert Bottom n=.012
Culvert=2,8,8.95,69,.012,.5,1,10,1,10.93,5004.5,10.89,5004.5,Culvert #2  , 0 ,14
Culvert Bottom n=.012
BC Design=,, 0 ,, 0 ,,,,,,
BC HTab HWMax=27.44

Type RM Length L Ch R = 1 ,12822.08,80.06,93.7,97.96
XS GIS Cut Line= 6
     3198704.974    13763561.225      3197179.15    13762218.441
     3196983.703    13762030.779     3196467.181    13761595.765
      3196000.47    13760812.543     3192988.389    13757810.905
#Sta/Elev= 30
 2459.35   21.74 2866.51   23.83 2974.88   24.23 3013.31   21.54 3073.02   21.69
  3119.6   24.31 3656.05   22.09 4169.41   23.38 4576.56    21.3 4627.59   21.17
 4721.29    24.2 4819.79   19.81 4922.73   19.56 4986.79   16.33 4989.77   13.23
 4990.05   10.91 5010.82   10.91 5011.76   13.95 5013.21   15.98 5030.24   19.25
 5390.87    21.3 6057.86   24.11 7294.62   22.79 7866.01    23.8 8055.67   22.09
 9704.11   25.65 9983.46   25.3610027.14   24.1810398.87   27.6410602.47   26.94
#Mann= 7 ,-1 , 0
 2459.35     .15       0 2866.51     .07       0 4169.41     .15       0
 4576.56     .07       0 4922.73    .015       0 5030.24     .07       0
 5390.87     .12       0
#XS Ineff= 2 , 0
       0    4976   19.35    5023       0   19.35
Permanent Ineff=
       F       F
#Block Obstruct= 2 ,-1
  4448.2 4701.35   22.91    2990    3090    22.5
Bank Sta=4922.73,5030.24
XS Rating Curve= 0
Exp/Cntr=.5,.3

Type RM Length L Ch R = 1 ,12728.39,1009.4,1130.06,1010.24
XS GIS Cut Line= 6
     3198752.335    13763491.577     3197233.352    13762159.577
      3197037.03    13761971.075     3196528.926    13761543.101
     3196064.047    13760762.954     3193062.805    13757773.696
#Sta/Elev= 30
 2431.95      23 2579.97    26.1 2695.62   22.92 2918.02   23.18 2984.69   21.35
 3081.39   24.29 3499.03   24.33 3603.32   21.85 3675.25    23.5 4133.19   23.94
  4438.5   23.06 4538.24    20.6 4681.02   24.16  4783.2   19.74 4922.73   19.56
 4999.75   11.25 5011.18   13.28 5013.21   15.98 5080.69    19.8 5348.35    21.4
 5478.87   23.55 5598.32   22.12  6201.3    24.1 8046.64    21.9 9069.28   23.63
 9202.93   25.79 9293.54   24.11 9948.78   23.7510316.93   27.7110533.07   26.68
#Mann= 7 ,-1 , 0
 2431.95     .15       0 2918.02     .07       0 4133.19     .15       0
 4538.24     .07       0 4922.73    .035       0 5080.69     .07       0
 5348.35     .12       0
#Block Obstruct= 2 ,-1
 4363.63 4688.81   23.12    2940    3060    22.3
Bank Sta=4922.73,5080.69
XS Rating Curve= 0
Exp/Cntr=.3,.1

Type RM Length L Ch R = 1 ,11598.32,1089.25,947.07,768.04
XS GIS Cut Line= 6
     3199398.673    13762758.874     3197817.454    13761358.188
     3197293.444    13760876.956     3197008.346    13760647.673
     3195024.526    13759116.013     3193318.409    13757610.304
#Sta/Elev= 30
 2098.34   22.32 2496.92   22.92 2617.66   20.54 2736.07   22.78 3054.93   22.65
 3294.08   23.99 3884.69   22.47 4042.21    24.6 4169.06   22.91 4201.88   19.77
 4250.67   20.45 4358.91   23.72 4474.64   18.36 4619.55   20.28 4723.74   18.85
 4880.06   23.39  4933.8   20.93 4971.62    8.53 4995.73   17.45 5036.28   20.76
  5115.1   24.67 5326.34    26.1 5680.36   21.71 6154.28   23.76 6746.93   23.31
 6964.63   20.45  7359.6   21.58 8316.19   21.22 9990.23   24.8610069.95   25.05
#Mann= 11 ,-1 , 0
 2098.34     .12       0 2496.92     .07       0 2736.07     .12       0
 3054.93     .07       0 3294.08     .15       0 4250.67     .07       0
  4933.8    .035       0 5036.28     .07       0  7359.6     .15       0
 8316.19     .07       0 9990.23     .12       0
#XS Ineff= 1 ,-1
    4390    4800    21.9
Permanent Ineff=
       F
#Block Obstruct= 2 ,-1
 4024.16 4357.01   23.61    2530    2730      22
Bank Sta=4933.8,5036.28
XS Rating Curve= 0
Exp/Cntr=.3,.1

Type RM Length L Ch R = 1 ,10651.25,457.87,643.74,724.29
XS GIS Cut Line= 6
     3200287.389    13761742.005     3198225.188       13760204.
     3197974.497    13760121.877     3197733.642    13760144.624
     3197482.038    13760046.501     3193915.357    13757231.751
#Sta/Elev= 30
 2027.42   21.86 2116.69   20.35 2427.97   22.03 2554.15   19.68 2659.04   23.23
 3623.98   22.08 3841.69   19.33 3889.06   21.85 3932.26   19.97 3988.92   22.13
 4069.47      19 4303.26   22.22 4367.57    18.8 4462.02   18.04 4737.26   19.51
 4964.94   17.25 4987.49   11.29 4988.88     8.2 4990.63    7.71 5036.68    17.7
 5573.59   21.89 5638.38   19.43 7058.82    18.6 7451.83   20.64 8097.16   18.42
 8456.18   21.43    9520   21.03 9645.46   24.58 9790.68   22.38 9922.73   23.15
#Mann= 4 ,-1 , 0
 2027.42     .07       0 2659.04     .15       0 4964.94    .035       0
 5036.68     .07       0
#XS Ineff= 1 ,-1
    5600    8380      20
Permanent Ineff=
       F
#Block Obstruct= 2 ,-1
 3624.68 4302.49   22.04    2400    2610      22
Bank Sta=4964.94,5036.68
XS Rating Curve= 0
Exp/Cntr=.3,.1

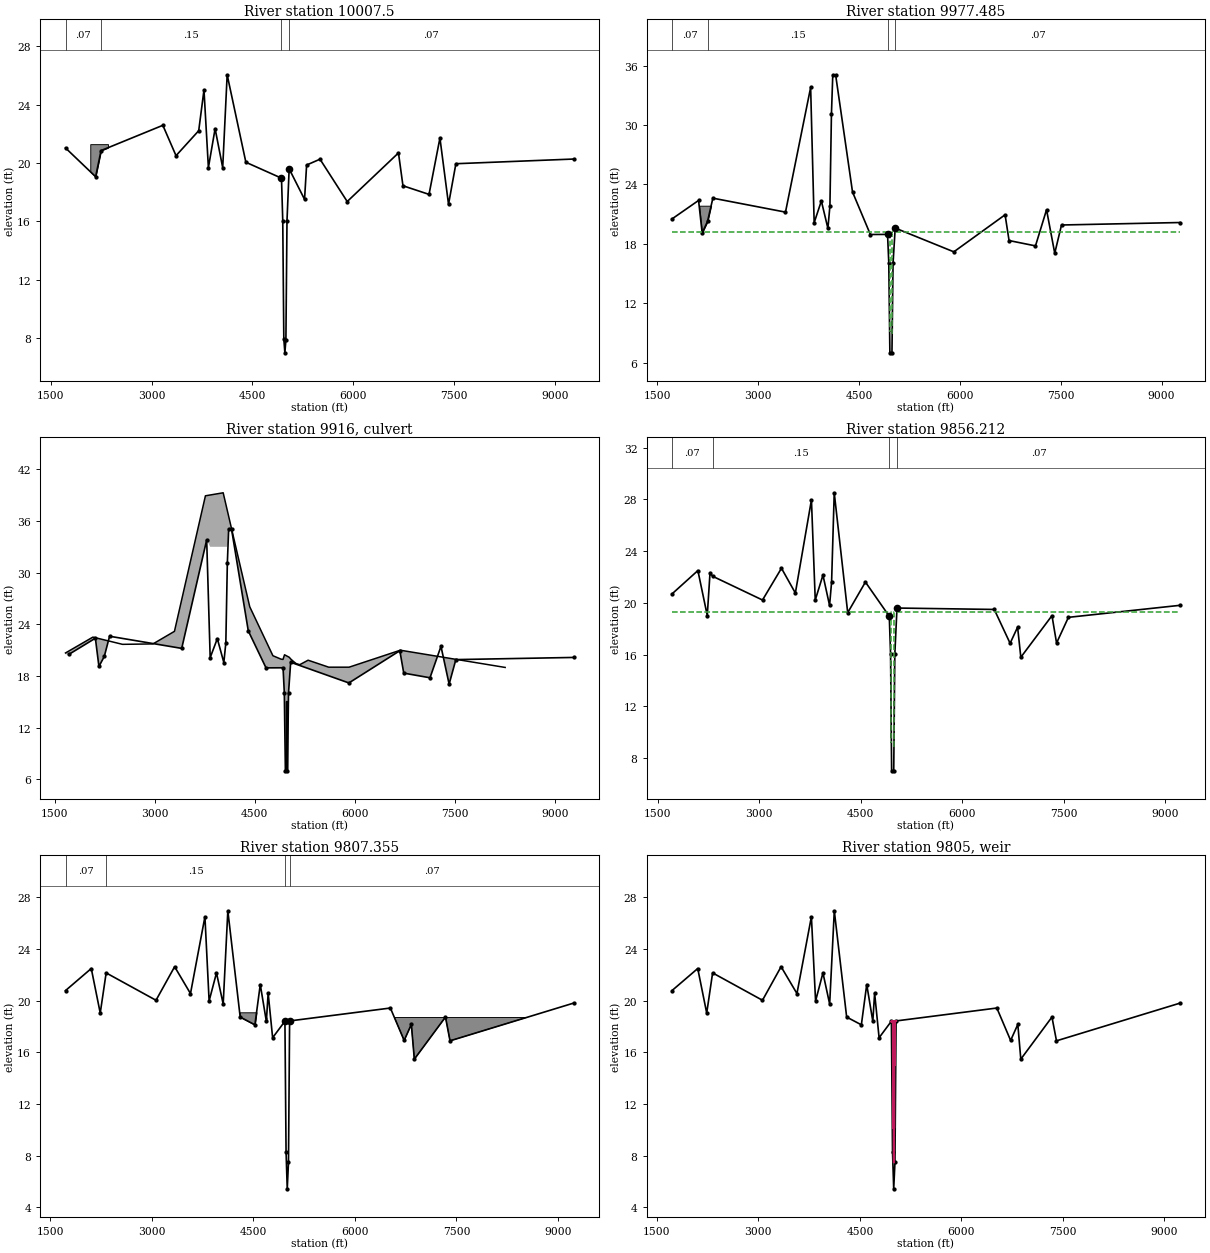
Type RM Length L Ch R = 1 ,10007.5 ,39.04,30.02,32.51
XS GIS Cut Line= 6
     3200362.431    13761617.674     3199155.771    13760618.827
     3198424.356     13759970.26     3197422.233    13759109.336
     3197242.665     13758995.38     3194465.312    13756899.493
#Sta/Elev= 30
  1720.1   21.03 2168.01   19.06 2249.12   20.85 3168.05   22.58 3364.09    20.5
 3701.55   22.21    3780      25 3845.71   19.68 3945.43   22.35 4058.48   19.68
 4124.84   26.04 4403.11   20.05 4933.02   18.96 4951.79   16.05 4967.62    7.95
  4983.3       7 4998.53    7.88 5014.81   16.04 5046.98    19.6 5275.91   17.51
 5306.75   19.86 5505.83   20.26  5910.5   17.36 6673.13   20.69 6739.86   18.44
 7127.73   17.85  7289.9   21.71 7417.79   17.17 7527.25   19.95 9277.48   20.27
#Mann= 4 ,-1 , 0
  1720.1     .07       0 2249.12     .15       0 4933.02    .015       0
 5046.98     .07       0
#XS Ineff= 1 ,-1
    5520    9040    19.5
Permanent Ineff=
       F
#Block Obstruct= 1 ,-1
 2088.43    2352   21.29
Bank Sta=4933.02,5046.98
XS Rating Curve= 0
Exp/Cntr=.5,.3

Type RM Length L Ch R = 1 ,9977.485,139.43,121.27,121.99
XS GIS Cut Line= 6
     3200381.561    13761594.564     3199175.293    13760596.043
     3198443.911    13759947.504     3197440.012    13759085.088
     3197259.765    13758970.701     3194483.383    13756875.546
#Sta/Elev= 30
 1715.73   20.52 2111.54   22.39 2164.61   19.11 2244.84   20.27 2324.23   22.62
 3404.75   21.21 3778.85    33.8 3831.26   20.14 3938.24   22.34 4035.77   19.57
 4065.75   21.85 4088.22   31.08 4108.25   35.08 4150.83   35.06 4402.06   23.24
 4667.71   18.95 4923.02   18.96 4941.79   16.05 4957.79       7 4988.68       7
 5004.81   16.04 5036.98    19.6 5909.24    17.2 6671.87   20.94 6730.97   18.34
 7124.06    17.8 7288.64   21.45 7410.58   17.06 7511.36   19.91 9274.47   20.16
#Mann= 4 ,-1 , 0
 1715.73     .07       0 2244.84     .15       0 4923.02    .015       0
 5036.98     .07       0
#XS Ineff= 2 , 0
       0    4954    19.2    4992       0    19.2
Permanent Ineff=
       F       F
#Block Obstruct= 1 ,-1
 2064.91    2352   21.86
Bank Sta=4923.02,5036.98
XS Rating Curve= 0
Exp/Cntr=.5,.3

Type RM Length L Ch R = 2 ,9916    ,,,
BEGIN DESCRIPTION:
528
END DESCRIPTION:
Bridge Culvert--1,0,-1,-1, 0
Deck Dist Width WeirC Skew NumUp NumDn MinLoCord MaxHiCord MaxSubmerge Is_Ogee
1,120,2.6,0, 23, 23, , , .95, 0, 0,0,,
    1664    2074    2518    2974    3296    3760    4026    4100    4424    4771
    4893    4922 4945.06 5015.39 5041.63 5080.99 5120.68    5173    5298    5607
    5912    6680    8250
   20.68   22.52   21.68   21.73   23.19   38.92   39.27   36.81   26.04   20.36
   19.96   19.93   20.47   20.18   19.95   19.68   19.44   19.32   19.84   19.03
   19.03      21      19
                                              33      33      33
                                                                                
                        
    1664    2074    2518    2974    3296    3760    4026    4100    4424    4771
    4893    4922 4945.06 5015.39 5041.63 5080.99 5120.68    5173    5298    5607
    5912    6680    8250
   20.68   22.52   21.68   21.73   23.19   38.92   39.27   36.81   26.04   20.36
   19.96   19.93   20.47   20.18   19.95   19.68   19.44   19.32   19.84   19.03
   19.03      21      19
                                              33      33      33
                                                                                
                        
Multiple Barrel Culv=2,8,8,120,.012,.5,1,10,1,7.07,6.96, 3,Culvert #1  , 0 ,1
    4964    4964    4973    4973    4982    4982
Culvert Bottom n=.012
BC Design=,, 0 ,, 0 ,,,,,,
BC HTab HWMax=35.08

Type RM Length L Ch R = 1 ,9856.212,44.85,48.86,30.1
XS GIS Cut Line= 6
     3200441.929     13761534.66     3198645.855    13759959.745
     3198437.012    13759761.409      3198210.43    13759595.576
     3197433.482    13758919.192      3194641.92    13756781.134
#Sta/Elev= 30
 1713.21   20.69 2095.93    22.5  2234.4   19.02 2275.21   22.33 2313.54   22.06
 3050.48   20.22 3330.59   22.68 3535.76   20.76 3773.28   27.97 3829.52   20.22
 3943.36   22.15 4040.86    19.8  4070.9   21.61 4109.89   28.52 4308.93   19.24
 4570.54   21.61 4923.02   18.96 4941.79   16.05 4957.79       7 4988.68       7
 5004.81   16.04 5036.98    19.6 6473.65   19.49 6707.67   16.87 6818.36   18.12
 6866.01   15.79 7326.09   19.01 7393.96   16.89 7568.84   18.88 9217.32   19.81
#Mann= 4 ,-1 , 0
 1713.21     .07       0 2313.54     .15       0 4923.02    .015       0
 5036.98     .07       0
#XS Ineff= 2 , 0
       0    4954   19.28    4992       0   19.28
Permanent Ineff=
       F       F
Bank Sta=4923.02,5036.98
XS Rating Curve= 0
Exp/Cntr=.5,.3

Type RM Length L Ch R = 1 ,9807.355,377.08,167.62,50.91
XS GIS Cut Line= 6
     3200445.225      13761530.9     3198649.226    13759956.051
     3198195.663    13759525.307     3197977.043    13759327.473
     3197710.383     13759130.15     3194644.961    13756777.165
#Sta/Elev= 30
 1723.99   20.78 2104.67   22.49 2237.11   19.04 2324.41   22.15 3060.93   20.03
 3335.97   22.63  3570.3   20.55 3783.73    26.5 3845.48   19.98 3954.36   22.15
  4053.4   19.74    4122   26.96 4304.56   18.73 4521.83   18.13  4601.2   21.25
 4691.01    18.4 4717.74   20.58 4783.74   17.13 4965.43   18.41 4982.21     8.3
 4999.63    5.43 5017.98    7.47 5034.57   18.43 6523.23   19.43 6726.92   16.92
 6833.04   18.16 6877.22   15.47  7337.3   18.73 7404.42   16.89 9229.19   19.81
#Mann= 4 ,-1 , 0
 1723.99     .07       0 2324.41     .15       0 4965.43    .015       0
 5034.57     .07       0
#Block Obstruct= 3 ,-1
    4260    4590    19.1    6000    8640    18.7    4650    4700    18.7
Bank Sta=4965.43,5034.57
XS Rating Curve= 0
Exp/Cntr=.5,.3

Type RM Length L Ch R = 5 ,9805    ,,,
BEGIN DESCRIPTION:
Downstream of 528
END DESCRIPTION:
IW Pilot Flow=0
#Inline Weir SE= 17
4965.985   18.39 4977.14   18.414988.906    18.44989.169   14.924994.415   14.94
4994.606   10.814994.866   10.18 4997.84   10.174997.934    7.535000.396    7.46
 5003.88    7.515004.121   10.175007.136   10.175007.325   14.955012.896   14.96
5013.015   18.43 5034.57   18.43
IW Dist,WD,Coef,Skew,MaxSub,Min_El,Is_Ogee,SpillHt,DesHd
2,.1,3.3,0,.95,, 0 ,,,0,0,

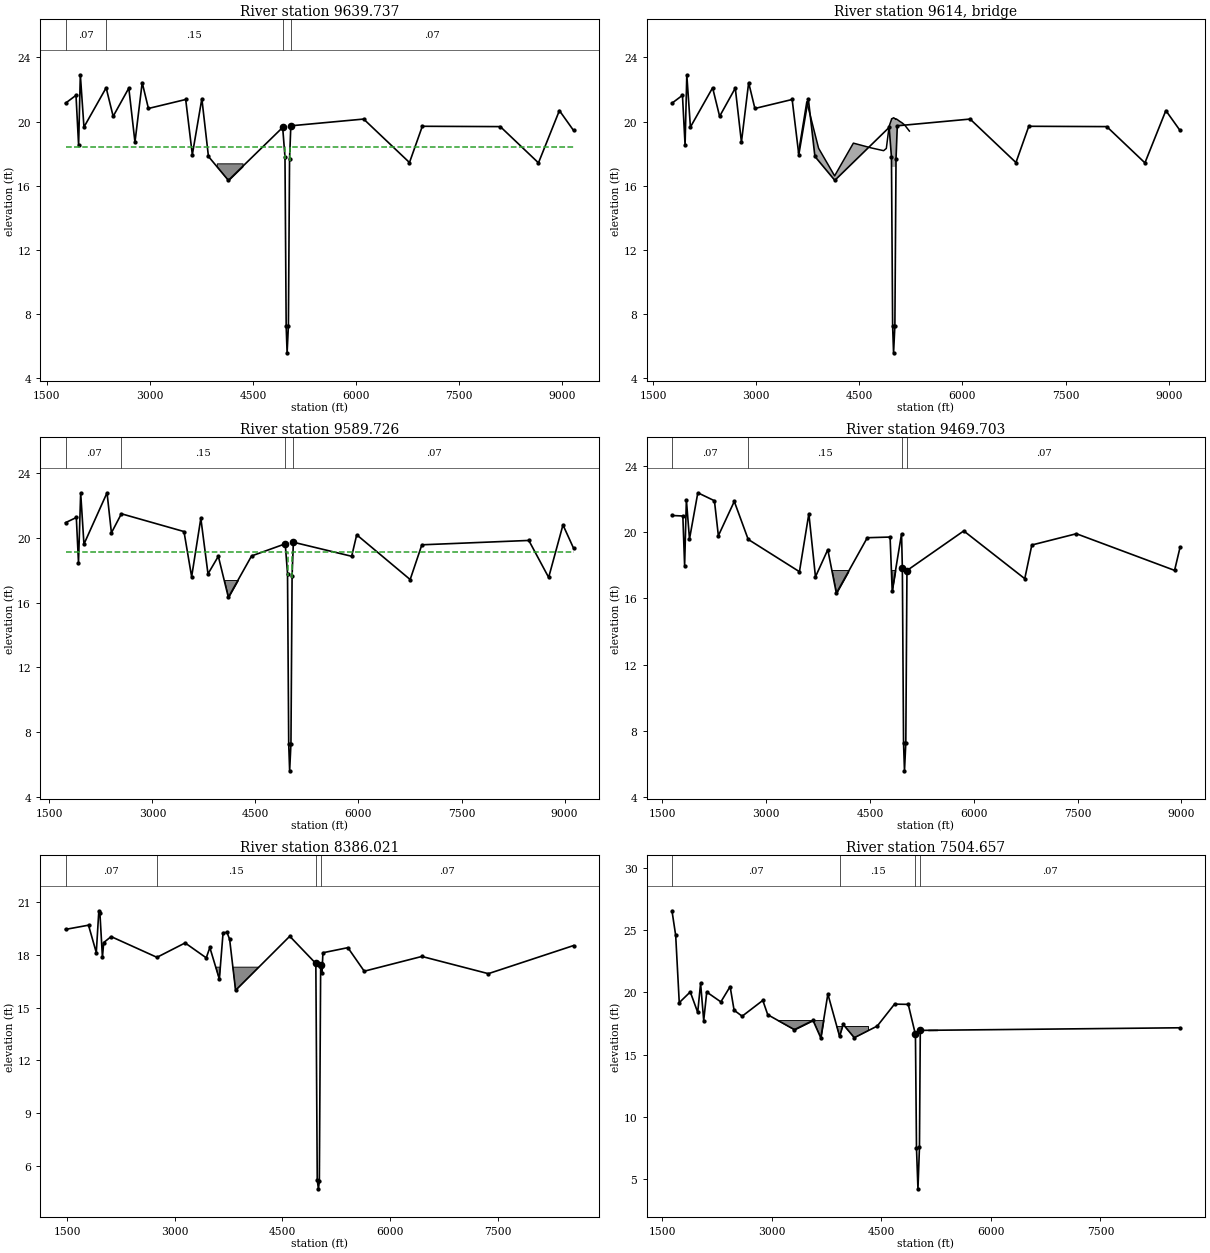
Type RM Length L Ch R = 1 ,9639.737,70.65,50.01,53.46
XS GIS Cut Line= 6
     3200688.154    13760874.154      3198657.58    13759191.081
     3198269.138     13759196.98     3198105.556    13759203.059
     3197890.521    13759218.411     3194824.352    13756672.322
#Sta/Elev= 30
 1773.98   21.15 1926.62   21.64 1964.56   18.53 1989.73   22.92 2042.33   19.66
 2365.23   22.11 2467.15   20.33    2695   22.09 2784.36   18.72 2889.52   22.43
 2980.29   20.82 3522.35   21.38 3618.96   17.94 3757.45   21.43 3853.33   17.83
 4142.99   16.34 4933.21   19.64 4966.76    17.8 4984.05    7.26 4997.59    5.59
 5016.71    7.28 5033.24   17.67 5051.91   19.74 6111.13   20.16 6777.98   17.45
  6964.6   19.71    8099   19.69 8654.27   17.43 8958.67   20.69 9164.63   19.45
#Mann= 4 ,-1 , 0
 1773.98     .07       0 2365.23     .15       0 4933.21    .015       0
 5051.91     .07       0
#XS Ineff= 2 , 0
       0    4967    18.4    5033       0    18.4
Permanent Ineff=
       F       F
#Block Obstruct= 1 ,-1
    3975    4350    17.4
Bank Sta=4933.21,5051.91
XS Rating Curve= 0
Exp/Cntr=.5,.3

Type RM Length L Ch R = 3 ,9614    ,,,
BEGIN DESCRIPTION:
ACCESS RD
END DESCRIPTION:
Bridge Culvert--1,0,-1,-1, 0
Deck Dist Width WeirC Skew NumUp NumDn MinLoCord MaxHiCord MaxSubmerge Is_Ogee
1,48,2.6,0, 19, 19, , , .95, 0, 0,0,,
    3614    3735    3907    4140    4413    4675    4853 4892.33    4933 4967.68
 4967.82 4999.56 5031.35 5031.36 5051.41 5082.98 5119.52    5159    5228
   18.06   21.24   18.34   16.62   18.66   18.36   18.19   18.33   19.71   20.14
   20.17   20.24   20.14   20.17   20.13   20.03   19.93   19.79   19.41
                                                                           17.18
   17.18   17.18   17.18   17.18
    3614    3735    3907    4140    4413    4675    4853 4892.33    4933 4967.68
 4967.82 4999.56 5031.35 5031.36 5051.41 5082.98 5119.52    5159    5228
   18.06   21.24   18.34   16.62   18.66   18.36   18.19   18.33   19.71   20.14
   20.17   20.24   20.14   20.17   20.13   20.03   19.93   19.79   19.41
                                                                           17.18
   17.18   17.18   17.18   17.18
BR Coef=-1 , 1 , 0 ,1.25, 0 ,,,.8,-1,2,6,
WSPro=,,,, 1 ,,,, 0 ,,,, 0 ,,,,-1 ,-1 ,-1 , 0 , 0 , 0 , 0 , 0
BC Design=,, 0 ,, 0 ,,,,,,
BC HTab HWMax=22.92

Type RM Length L Ch R = 1 ,9589.726,141.03,120.02,128.4
XS GIS Cut Line= 6
     3200720.062    13760835.659      3198655.97    13759123.876
     3198268.509     13759139.83     3198103.041    13759153.118
     3197906.926    13759167.042     3194856.294    13756633.855
#Sta/Elev= 30
 1734.13   20.95 1891.67   21.27 1923.22   18.48 1955.13   22.79 2002.61   19.62
 2338.91    22.8 2402.59   20.32 2547.82    21.5 3459.31    20.4 3570.68    17.6
 3704.54   21.22 3808.75   17.78 3959.39   18.87 4105.22   16.33 4443.28   18.89
 4933.21   19.64 4966.76    17.8 4984.05    7.26 4997.59    5.59 5016.71    7.28
 5033.24   17.67 5051.91   19.74 5900.72   18.87 5974.17    20.2 6752.38   17.43
 6922.91   19.58 8479.92   19.85 8768.98   17.56 8977.25   20.81 9131.35   19.37
#Mann= 4 ,-1 , 0
 1734.13     .07       0 2547.82     .15       0 4933.21    .015       0
 5051.91     .07       0
#XS Ineff= 2 , 0
       0    4967   19.11    5033       0   19.11
Permanent Ineff=
       F       F
#Block Obstruct= 1 ,-1
    3990    4280    17.4
Bank Sta=4933.21,5051.91
XS Rating Curve= 0
Exp/Cntr=.5,.3

Type RM Length L Ch R = 1 ,9469.703,776.07,1083.68,1141.59
XS GIS Cut Line= 6
      3200796.64     13760743.27     3198690.158    13759003.079
     3198307.255    13759016.754     3198097.006    13759033.259
     3197946.298    13759043.758     3194973.363    13756573.329
#Sta/Elev= 30
 1636.99   20.99 1794.16   20.96 1819.71   17.97 1845.21   21.94 1890.16   19.57
 2010.59   22.36 2250.64   21.88 2307.58   19.77 2537.52   21.84 2738.42   19.55
 3479.42    17.6 3615.51    21.1 3710.86   17.29 3889.16   18.93 4012.82    16.3
 4460.03   19.65 4789.57   19.69 4819.74   16.45 4955.25   19.89 4966.76    17.8
 4984.05    7.26 4997.59    5.59 5016.71    7.28 5033.24   17.67  5854.2   20.06
 6735.87   17.18 6838.09   19.21 7482.01   19.89 8901.35   17.68 8979.83   19.06
#Mann= 4 ,-1 , 0
 1636.99     .07       0 2738.42     .15       0 4966.76    .015       0
 5033.24     .07       0
#Block Obstruct= 2 ,-1
    3912    4185    17.7    4800    4865    17.7
Bank Sta=4966.76,5033.24
XS Rating Curve= 0
Exp/Cntr=.3,.1

Type RM Length L Ch R = 1 ,8386.021,191.78,881.36,731.88
XS GIS Cut Line= 6
     3201411.915    13760445.259     3198794.184    13758273.637
     3198725.747    13758216.883     3198674.989     13758172.64
     3198602.869    13758113.346      3195908.42    13755984.469
#Sta/Elev= 30
  1475.3   19.45 1796.15   19.69  1904.6   18.13 1940.07   20.51 1954.61   20.41
 1990.27   17.87 2007.99    18.7 2111.51   19.04 2750.57   17.86 3143.34   18.68
 3438.11   17.83 3487.99   18.42 3620.73   16.62 3672.65   19.26 3726.66   19.28
 3763.97   18.89 3847.09   15.98 4602.48   19.06 4966.33   17.51 4985.99    5.17
 5002.35    4.68 5015.28    5.11 5033.67   17.45 5052.97   16.98  5064.8   18.12
 5413.09   18.41 5641.35   17.07  6445.1   17.91 7371.85   16.93 8560.12   18.53
#Mann= 4 ,-1 , 0
  1475.3     .07       0 2750.57     .15       0 4966.33    .015       0
 5033.67     .07       0
#Block Obstruct= 1 ,-1
    3560    4230    17.3
Bank Sta=4966.33,5033.67
XS Rating Curve= 0
Exp/Cntr=.3,.1

Type RM Length L Ch R = 1 ,7504.657,96.35,88.57,85.14
XS GIS Cut Line= 6
     3201458.825    13760271.021     3199120.006    13758314.186
     3199334.227    13758034.451     3199357.369    13758002.142
     3199187.021    13757771.366     3196968.828    13755425.845
#Sta/Elev= 30
 1632.96   26.55 1683.84   24.57 1732.68   19.17 1883.61   20.03 1985.23   18.39
 2024.95   20.72 2067.54   17.73 2109.11   20.02 2302.41   19.23 2429.18   20.46
 2483.59   18.56 2594.06   18.08 2876.82   19.35 2944.26    18.2 3309.63      17
 3564.16   17.74 3670.64   16.34 3767.64   19.86 3928.67   16.45  3977.8   17.42
 4129.64   16.35 4444.03   17.29 4680.37   19.05 4868.24   19.03 4966.83   16.61
 4981.18    7.49 5001.19    4.21 5021.83    7.55 5033.17   16.94 8589.66   17.15
#Mann= 4 ,-1 , 0
 1632.96     .07       0 3928.67     .15       0 4966.83    .015       0
 5033.17     .07       0
#Block Obstruct= 5 ,-1
 3069.13 3774.73   17.77    3880    4324   17.25    5140    5265      17
    5370    5960    16.8    7031    8000    16.8
Bank Sta=4966.83,5033.17
XS Rating Curve= 0
Exp/Cntr=.3,.1