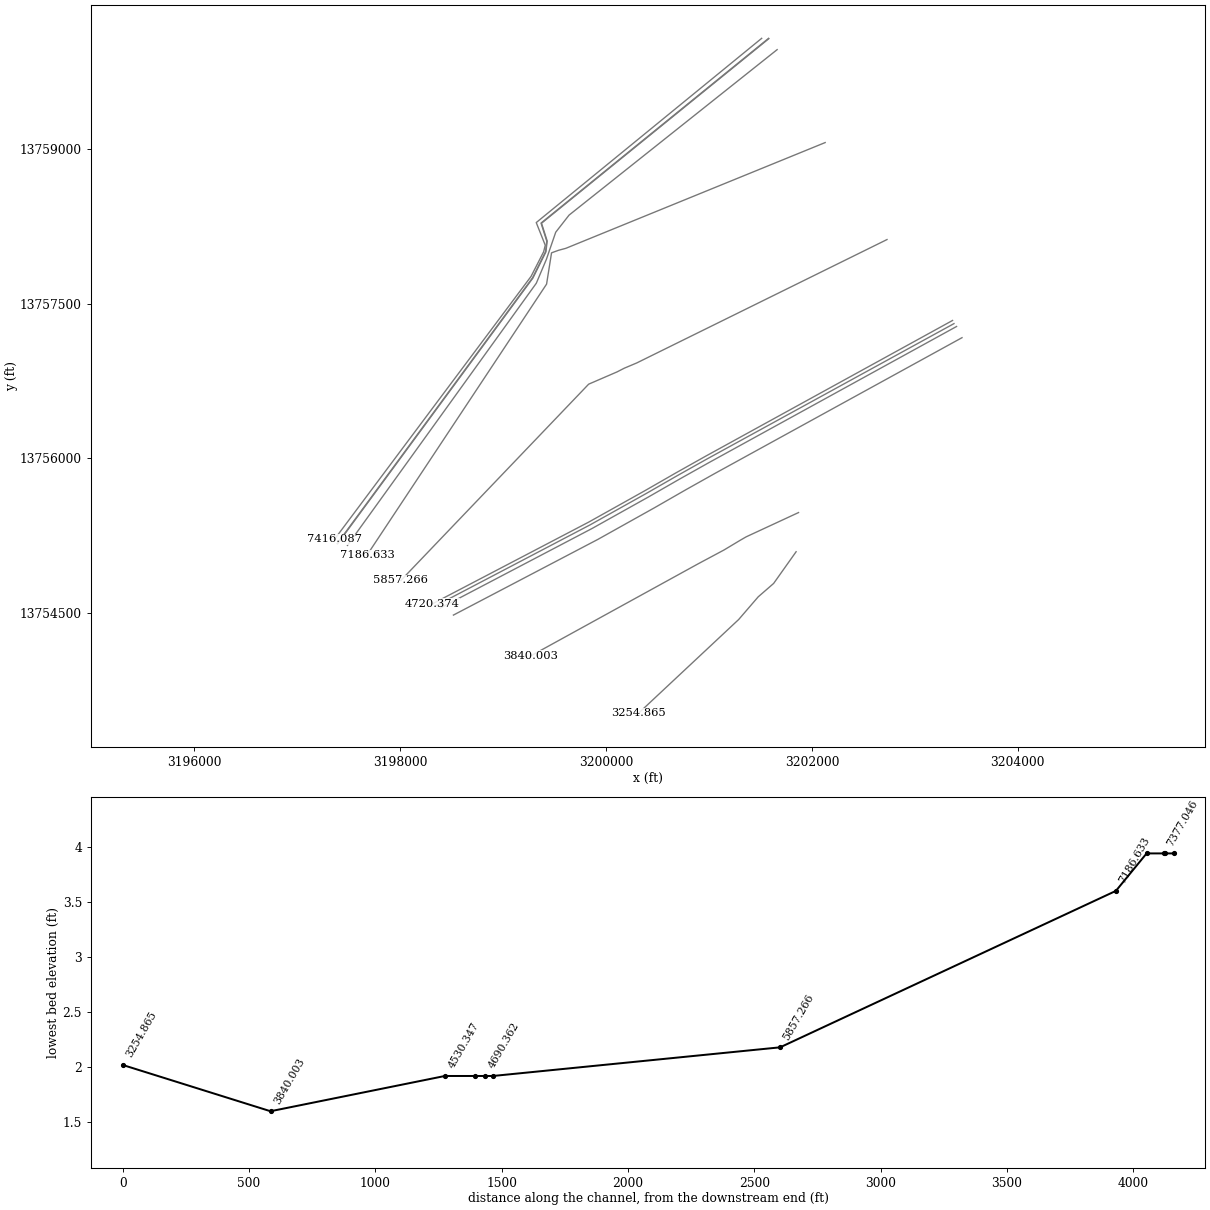
HEC-RAS study A111_00_00.prj: A111-00-00

--- A111_00_00.g01 (geometry) --- (continued)

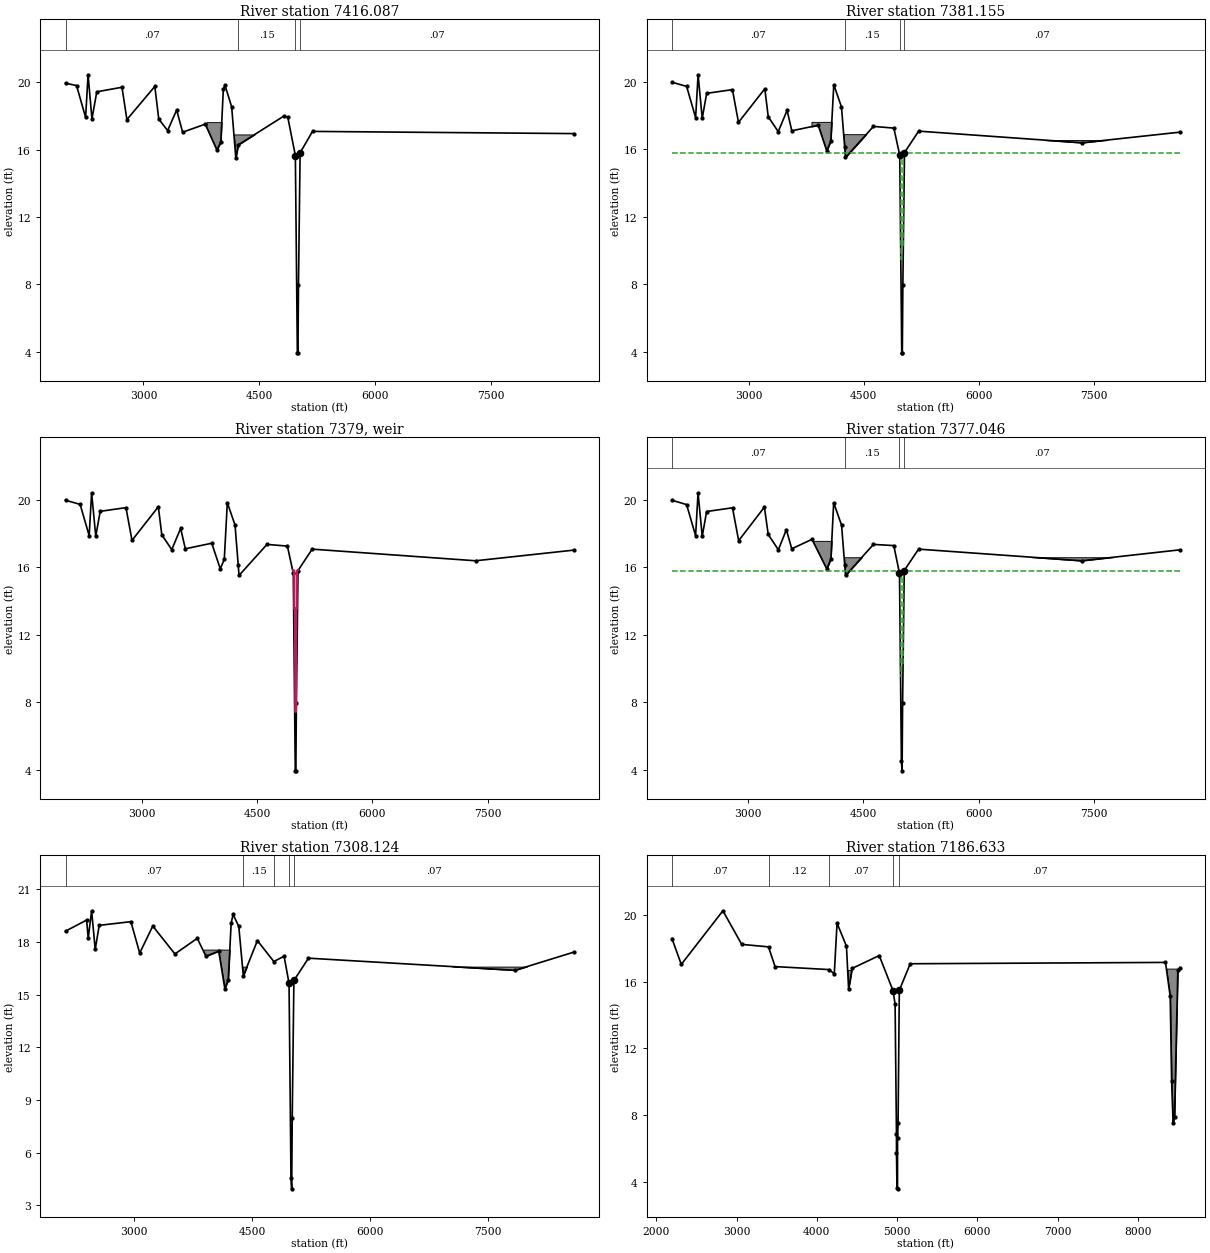
Type RM Length L Ch R = 1 ,7416.087,57.1,34.93,24.74
XS GIS Cut Line= 6
     3201512.486    13760076.895     3199323.597    13758287.948
     3199411.159    13758067.716     3199395.239    13758004.035
     3199273.182    13757765.229     3197365.376    13755213.268
#Sta/Elev= 30
 1989.89   19.94 2133.17    19.8 2250.38   17.91 2282.34   20.44 2332.61   17.82
 2395.47   19.43 2722.18    19.7 2785.47   17.78  3147.6   19.75 3198.58   17.81
  3313.6   17.13 3430.72   18.35 3507.84   17.03 3800.62   17.51 3951.83   15.98
 4002.45   16.43 4035.78   19.58 4056.01   19.84 4143.92   18.53 4197.55   15.49
 4228.87   16.28  4816.9   17.98 4870.76   17.93  4969.2   15.65 4995.08    3.94
 5002.86    3.94 5009.73    7.99  5030.8   15.81 5191.67   17.08 8575.12   16.95
#Mann= 4 ,-1 , 0
 1989.89     .07       0 4228.87     .15       0  4969.2    .015       0
  5030.8     .07       0
#Block Obstruct= 3 ,-1
 3818.83 4135.88   17.63    4156    4590    16.9    5920    7919   16.55
Bank Sta=4969.2,5030.8
XS Rating Curve= 0
Exp/Cntr=.5,.3

Type RM Length L Ch R = 1 ,7381.155,4.47,4.11,4.36
XS GIS Cut Line= 6
     3201579.452    13760076.677     3199370.135    13758283.009
     3199425.783    13758108.111     3199413.549    13758004.378
     3199287.543    13757751.261     3197391.022    13755171.188
#Sta/Elev= 30
 2001.77   19.98 2192.62   19.73 2309.92   17.88 2341.91   20.42 2395.83   17.84
 2453.66   19.32 2789.33   19.54 2868.13    17.6 3211.14   19.59 3256.21   17.93
 3386.12   17.05 3501.56   18.31 3562.89    17.1 3907.06   17.43 4018.04   15.91
  4070.5   16.48 4109.81   19.83 4210.26   18.51  4252.1   16.11 4262.32   15.52
 4626.62   17.36 4892.41   17.26  4969.2   15.65 4995.08    3.94 5002.86    3.94
 5009.73    7.99  5030.8   15.81 5215.41   17.08 7344.27   16.39 8620.39   17.02
#Mann= 4 ,-1 , 0
 2001.77     .07       0  4252.1     .15       0  4969.2    .015       0
  5030.8     .07       0
#XS Ineff= 2 , 0
       0 4982.93   15.81 5015.82       0   15.81
Permanent Ineff=
       F       F
#Block Obstruct= 3 ,-1
 3818.83 4135.88   17.63    4230    4590    16.9    5920    7919   16.55
Bank Sta=4969.2,5030.8
XS Rating Curve= 0
Exp/Cntr=.5,.3

Type RM Length L Ch R = 5 ,7379    ,,,
IW Pilot Flow=0
#Inline Weir SE= 14
4966.678   15.824982.919   15.814982.977   13.544991.778   13.554991.958   12.49
4994.889   12.474994.889    7.455003.922    7.455003.922   12.485007.199   12.45
5007.254   13.565015.821   13.575015.822    15.8    5031   15.83
IW Dist,WD,Coef,Skew,MaxSub,Min_El,Is_Ogee,SpillHt,DesHd
2,.1,4.55,0,.95,, 0 ,,,3,3,

Type RM Length L Ch R = 1 ,7377.046,99.49,68.922,56.93
XS GIS Cut Line= 6
     3201581.973    13760073.572     3199374.761    13758281.612
     3199429.859    13758108.523      3199417.44    13758003.219
      3199290.97     13757749.17     3197394.245    13755168.819
#Sta/Elev= 30
 2005.82   19.98 2196.25   19.72 2313.55   17.88 2345.54   20.42 2399.83   17.84
 2457.14   19.31 2794.24   19.53 2874.28   17.58 3209.43   19.57 3259.52   17.95
 3391.28   17.04  3495.9   18.23  3565.8    17.1 3829.08   17.66 4022.47    15.9
 4075.43    16.5 4112.05   19.83 4214.68    18.5 4255.59   16.15 4266.52   15.52
 4629.88   17.36 4894.89   17.29  4969.2   15.65 4993.93    4.54 5002.86    3.94
 5009.73    7.99  5030.8   15.81 5217.24   17.08 7341.38   16.39  8622.8   17.04
#Mann= 4 ,-1 , 0
 2005.82     .07       0 4255.59     .15       0  4969.2    .015       0
  5030.8     .07       0
#XS Ineff= 2 , 0
       0 4982.93   15.81 5015.82       0   15.81
Permanent Ineff=
       F       F
#Block Obstruct= 3 ,-1
 3818.83 4144.22   17.57    4210    4600    16.6    5920    7920    16.6
Bank Sta=4969.2,5030.8
XS Rating Curve= 0
Exp/Cntr=.5,.3

Type RM Length L Ch R = 1 ,7308.124,258.83,121.49,104.69
XS GIS Cut Line= 6
      3201662.73    13759967.181     3199642.181     13758360.31
     3199512.731    13758194.276     3199421.803    13757930.039
     3199324.184    13757698.988     3197490.424    13755153.258
#Sta/Elev= 30
 2126.85   18.62 2395.33   19.25 2415.48   18.22 2458.87   19.78 2504.67   17.58
 2555.56   18.95 2958.07   19.16 3070.32   17.37 3236.32   18.91 3518.27   17.32
 3802.22   18.21 3912.45   17.19 4074.82   17.48 4152.79   15.34 4195.82   15.84
 4233.39   19.08 4257.56   19.57 4330.22   18.89 4387.79   16.07 4566.81   18.08
 4775.38   16.89 4906.17   17.19  4969.2   15.65 4993.93    4.54 5002.86    3.94
 5009.73    7.99  5030.8   15.81 5216.53   17.08 7842.95   16.39 8586.69   17.42
#Mann= 5 ,-1 , 0
 2126.85     .07       0 4387.79     .15       0 4775.38     .07       0
  4969.2    .015       0  5030.8     .07       0
#Block Obstruct= 3 ,-1
 3818.83    4270   17.57    4333    4600    16.6    5920    8100    16.6
Bank Sta=4969.2,5030.8
XS Rating Curve= 0
Exp/Cntr=.5,.3

Type RM Length L Ch R = 1 ,7186.633,1312.65,1329.37,989.41
XS GIS Cut Line= 6
     3202128.974    13759064.753     3199610.703    13758037.826
      3199541.58    13758019.289     3199472.166    13757994.199
     3199423.946    13757690.335     3197679.186    13755057.263
#Sta/Elev= 30
 2195.21   18.58 2311.09   17.03 2829.94   20.24 3064.16   18.23 3398.17   18.08
 3479.87    16.9 4157.93   16.72 4217.61   16.45 4252.53    19.5 4369.57   18.12
 4396.51   15.56 4440.04   16.79 4778.11   17.56 4949.78   15.46 4975.77   14.66
 4992.86    6.88 4993.24    5.75 4999.15    3.64    5006     3.6 5006.23    6.62
 5013.01    7.55 5028.41   15.48 5164.11   17.07  8345.5   17.15 8404.08   15.13
 8422.07   10.03 8440.06    7.56 8458.06    7.88 8499.43   16.67 8526.57   16.83
#Mann= 5 ,-1 , 0
 2195.21     .07       0 3398.17     .12       0 4157.93     .07       0
 4949.78    .015       0 5028.41     .07       0
#Block Obstruct= 2 ,-1
 8344.83 8524.74   16.78    4365    4440    16.7
Bank Sta=4949.78,5028.41
XS Rating Curve= 0
Exp/Cntr=.3,.1

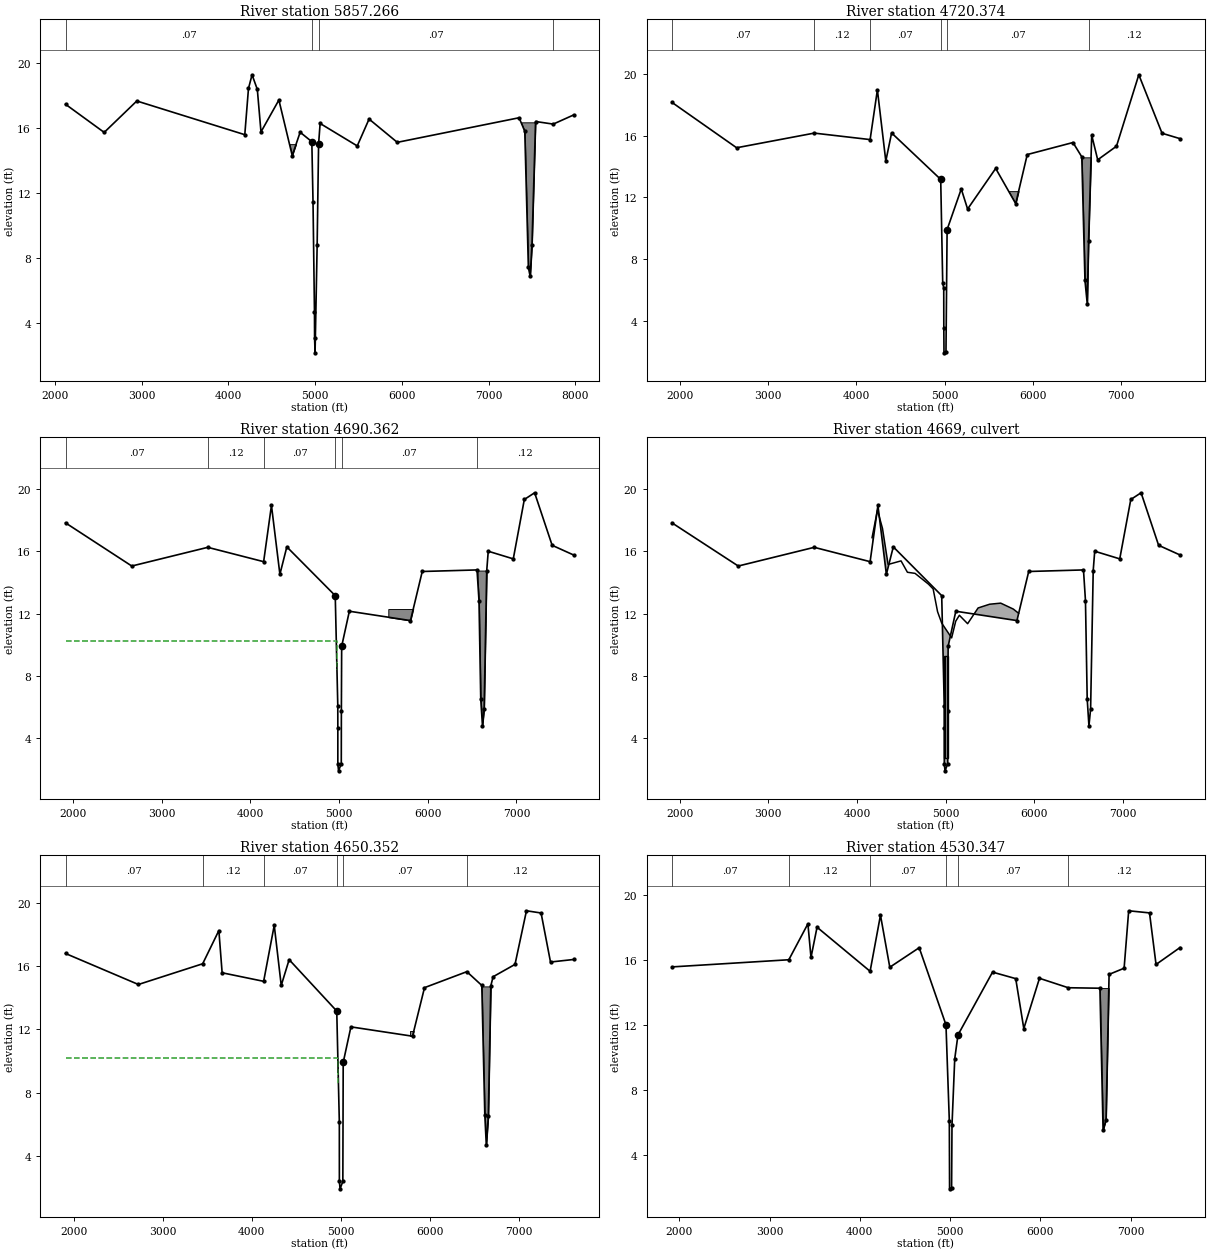
Type RM Length L Ch R = 1 ,5857.266,1114.29,1136.89,1170.69
XS GIS Cut Line= 6
     3202729.494     13758123.06     3200298.838    13756924.652
      3200177.75      13756873.6     3200108.443    13756838.067
     3199832.475     13756718.78     3198009.368    13754813.061
#Sta/Elev= 30
 2121.14   17.45 2567.13   15.72  2943.1   17.65 4188.11   15.58 4230.64   18.42
 4271.99   19.26 4332.68   18.36  4374.8   15.75 4581.22   17.71 4735.02    14.3
 4826.35   15.73 4961.06   15.15 4974.78   11.44  4991.5    4.67 4992.76     3.1
 4998.36    2.18 5022.35    8.79 5038.94      15 5056.62   16.27 5484.65   14.89
 5621.03   16.54 5946.14   15.11 7350.64   16.62 7416.13   15.79 7457.65    7.43
 7478.41    6.87 7499.17     8.8 7540.68   16.39 7744.14   16.23 7978.44   16.79
#Mann= 4 ,-1 , 0
 2121.14     .07       0 4961.06    .035       0 5038.94     .07       0
 7744.14     .12       0
#Block Obstruct= 2 ,-1
 7349.27 7542.65   16.34    4678    4804      15
Bank Sta=4961.06,5038.94
XS Rating Curve= 0
Exp/Cntr=.3,.1

Type RM Length L Ch R = 1 ,4720.374,30.01,30.01,30.19
XS GIS Cut Line= 6
     3203365.855     13757337.43     3200968.222    13756019.372
     3200679.246    13755857.125     3200379.191    13755684.799
     3199831.902    13755378.879     3198314.009    13754585.119
#Sta/Elev= 30
 1913.32   18.15 2645.43   15.21 3524.26   16.16 4157.13   15.74 4239.63   18.96
 4334.88   14.35 4400.49   16.17 4956.64   13.16 4979.34    6.46 4991.05    6.11
 4991.83    3.53 4993.96    1.92 5016.26    1.97 5029.16    9.91 5189.43   12.54
 5261.23   11.24 5579.26   13.87 5805.95   11.59  5936.7   14.77  6454.5   15.55
 6554.37   14.62 6590.33    6.61 6615.99    5.11 6631.08    9.14 6666.77   16.02
 6734.48   14.43 6947.23   15.31 7200.02   19.94 7463.27   16.15 7666.68    15.8
#Mann= 6 ,-1 , 0
 1913.32     .07       0 3524.26     .12       0 4157.13     .07       0
 4956.64    .035       0 5029.16     .07       0 6631.08     .12       0
#Block Obstruct= 2 ,-1
 6553.12 6660.72   14.59    5620    5960    12.4
Bank Sta=4956.64,5029.16
XS Rating Curve= 0
Exp/Cntr=.5,.3

Type RM Length L Ch R = 1 ,4690.362,40.01,40.01,40.26
XS GIS Cut Line= 6
     3203379.785    13757306.785     3200982.773    13755993.136
     3200694.057    13755831.035     3200393.981    13755658.697
     3199846.194    13755352.498     3198347.982    13754567.323
#Sta/Elev= 30
 1914.63   17.83  2662.1   15.06 3518.91   16.26 4149.16   15.34 4237.24   18.95
 4332.49   14.53 4410.68   16.29 4956.64   13.16 4985.38    6.11 4985.81    4.67
 4985.81    2.38 4993.96    1.92 5024.78    2.37  5025.8    5.78 5029.16    9.91
 5115.73   12.16 5805.13   11.56 5937.86   14.71 6555.59   14.81  6577.9   12.84
 6597.51    6.53  6617.1    4.81  6635.9    5.89 6665.25   14.77 6682.18   16.01
 6964.53   15.52 7089.06   19.33 7205.17   19.76 7402.81   16.39 7644.21   15.77
#Mann= 6 ,-1 , 0
 1914.63     .07       0 3518.91     .12       0 4149.16     .07       0
 4956.64    .035       0 5029.16     .07       0 6555.59     .12       0
#XS Ineff= 2 , 0
       0    4976   10.22    5033       0    9.72
Permanent Ineff=
       F       F
#Block Obstruct= 2 ,-1
 6562.93 6680.01   14.77    5555    5940    12.3
Bank Sta=4956.64,5029.16
XS Rating Curve= 0
Exp/Cntr=.5,.3

Type RM Length L Ch R = 2 ,4669    ,,,
BEGIN DESCRIPTION:
FOREST PARK CEMETARY RD
END DESCRIPTION:
Bridge Culvert--1,0,-1,-1, 0
Deck Dist Width WeirC Skew NumUp NumDn MinLoCord MaxHiCord MaxSubmerge Is_Ogee
10,22,2.6,0, 20, 20, , , .95, 0, 0,0,,
    4171    4232    4289    4352    4498    4570    4656    4807 4860.15 4909.97
 4956.46 5068.53 5114.58    5156    5249    5367    5497    5622    5764    5824
   16.88   18.65   17.47   15.16   15.39   14.66   14.59    13.9   13.59   12.13
    11.4   10.45   11.52    11.9   11.36   12.37   12.61   12.68    12.3   12.03
                                                                                
                                                                                
    4171    4232    4289    4352    4498    4570    4656    4807 4860.15 4909.97
 4956.46 5068.53 5114.58    5156    5249    5367    5497    5622    5764    5824
   16.88   18.65   17.47   15.16   15.39   14.66   14.59    13.9   13.59   12.13
    11.4   10.45   11.52    11.9   11.36   12.37   12.61   12.68    12.3   12.03
                                                                                
                                                                                
Multiple Barrel Culv=2,6.6,12,35,.012,.5,1,8,1,2.72,2.62, 3,Culvert #1  , 0 ,5
  4992.5  4992.5    5005    5005  5017.5  5017.5
Culvert Bottom n=.012
BC Design=,, 0 ,, 0 ,,,,,,
BC HTab HWMax=19.76

Type RM Length L Ch R = 1 ,4650.352,120.04,120.01,120.77
XS GIS Cut Line= 6
     3203404.859    13757278.925     3201002.174    13755958.156
     3200713.805    13755796.249     3200413.701    13755623.895
     3199865.249    13755317.325     3198391.661    13754544.675
#Sta/Elev= 30
 1907.63    16.8  2726.9   14.84 3449.53   16.15 3631.51   18.25 3668.23   15.58
 4134.82   15.04 4253.96   18.58 4332.54   14.78 4421.39   16.41 4956.64   13.16
  4985.7    6.12 4986.04     2.4 4993.96    1.92 5025.04    2.39 5029.16    9.91
 5115.73   12.16 5808.24   11.57 5942.95   14.64 6419.12   15.65 6587.01   14.78
 6620.88     6.6 6637.82    4.68 6660.47    6.51 6688.63   14.76 6714.15   15.33
 6960.35   16.11 7089.08    19.5 7253.44   19.36 7359.32   16.26 7618.38   16.42
#Mann= 6 ,-1 , 0
 1907.63     .07       0 3449.53     .12       0 4134.82     .07       0
 4956.64    .035       0 5029.16     .07       0 6419.12     .12       0
#XS Ineff= 2 , 0
       0    4976   10.22    5033       0    9.72
Permanent Ineff=
       F       F
#Block Obstruct= 2 ,-1
 6583.83 6692.52   14.72    5780    5830    11.9
Bank Sta=4956.64,5029.16
XS Rating Curve= 0
Exp/Cntr=.5,.3

Type RM Length L Ch R = 1 ,4530.347,686.57,690.34,684.14
XS GIS Cut Line= 6
     3203457.792    13757170.273     3201060.377    13755853.214
     3200773.047    13755691.891     3200472.862     13755519.49
     3199922.414    13755211.804     3198519.463     13754476.73
#Sta/Elev= 30
 1920.03   15.56  3213.9      16 3425.21   18.21 3459.41   16.14  3526.4      18
 4113.98   15.29 4228.77   18.74 4331.91   15.54  4657.6   16.74    4954      12
 4991.05    6.11 4993.96    1.92 5016.26    1.97 5020.66    5.82    5051    9.91
    5087   11.38 5469.71   15.24 5726.29   14.84 5815.82   11.77 5989.39   14.86
 6307.94   14.28 6658.63   14.25 6693.83    5.53 6726.37    6.17 6760.24    15.1
 6926.55   15.48 6977.13   19.01 7207.81   18.88 7280.15   15.71 7545.55   16.75
#Mann= 6 ,-1 , 0
 1920.03     .07       0  3213.9     .12       0 4113.98     .07       0
    4954    .035       0    5087     .07       0 6307.94     .12       0
#Block Obstruct= 1 ,-1
 6653.53 6762.97   14.26
Bank Sta=4954,5087
XS Rating Curve= 0
Exp/Cntr=.3,.1

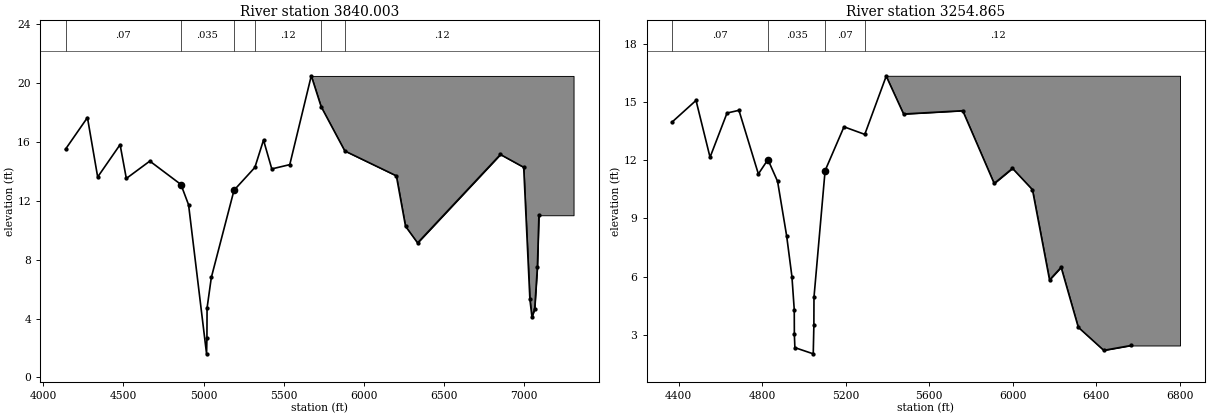
Type RM Length L Ch R = 1 ,3840.003,492.48,585.14,677.52
XS GIS Cut Line= 6
      3201870.41    13755472.187     3201361.903    13755236.455
     3201304.476    13755203.353     3201146.106    13755108.334
     3200896.248    13754974.864     3199266.862    13754078.764
#Sta/Elev= 30
 4138.83   15.51 4275.75   17.66 4339.59   13.62 4479.45   15.82 4518.38   13.52
    4665    14.7 4859.19   13.11 4906.84   11.73 5019.14     1.6  5021.4    2.68
 5022.21    4.71 5048.82    6.79 5190.44   12.72 5320.54   14.27 5374.46   16.13
 5426.13   14.17 5538.33   14.46 5672.58    20.5 5734.14    18.4 5881.85   15.39
 6203.44    13.7 6260.69   10.27 6335.99    9.14 6852.95   15.15 6998.13   14.28
 7036.76    5.32 7049.49    4.11 7066.61    4.64 7083.73    7.53 7093.11   11.02
#Mann= 6 ,-1 , 0
 4138.83     .07       0 4859.19    .035       0 5190.44     .07       0
 5320.54     .12       0 5734.14     .07       0 5881.85     .12       0
#Block Obstruct= 1 ,-1
 5672.96 7309.25   20.49
Bank Sta=4859.19,5190.44
XS Rating Curve= 0
Exp/Cntr=.3,.1

Type RM Length L Ch R = 1 ,3254.865,210.32,515.35,778.31
XS GIS Cut Line= 6
     3201846.836    13755091.649     3201628.545    13754783.888
     3201479.134    13754654.157     3201403.913    13754566.879
     3201289.419    13754433.874     3200315.161    13753522.259
#Sta/Elev= 30
 4367.46   13.96 4482.74   15.08 4549.92   12.15 4631.33   14.43 4688.44   14.57
 4781.51   11.29 4827.34   12.03 4873.58   10.91 4917.05     8.1 4942.39       6
 4953.55    4.29 4954.01    3.03 4956.55    2.34 5044.52    2.02 5047.58     3.5
 5048.05    4.93 5101.35   11.46 5191.93   13.72 5291.53   13.33 5394.24   16.33
 5477.58   14.38    5761   14.55 5911.74    10.8 5999.43   11.58 6095.16   10.48
 6177.05    5.83  6232.6    6.48 6314.83    3.39 6436.85     2.2 6567.62    2.45
#Mann= 4 ,-1 , 0
 4367.46     .07       0 4827.34    .035       0 5101.35     .07       0
 5291.53     .12       0
#Block Obstruct= 1 ,-1
 5397.46 6802.39   16.35
Bank Sta=4827.34,5101.35
XS Rating Curve= 0
Exp/Cntr=.3,.1