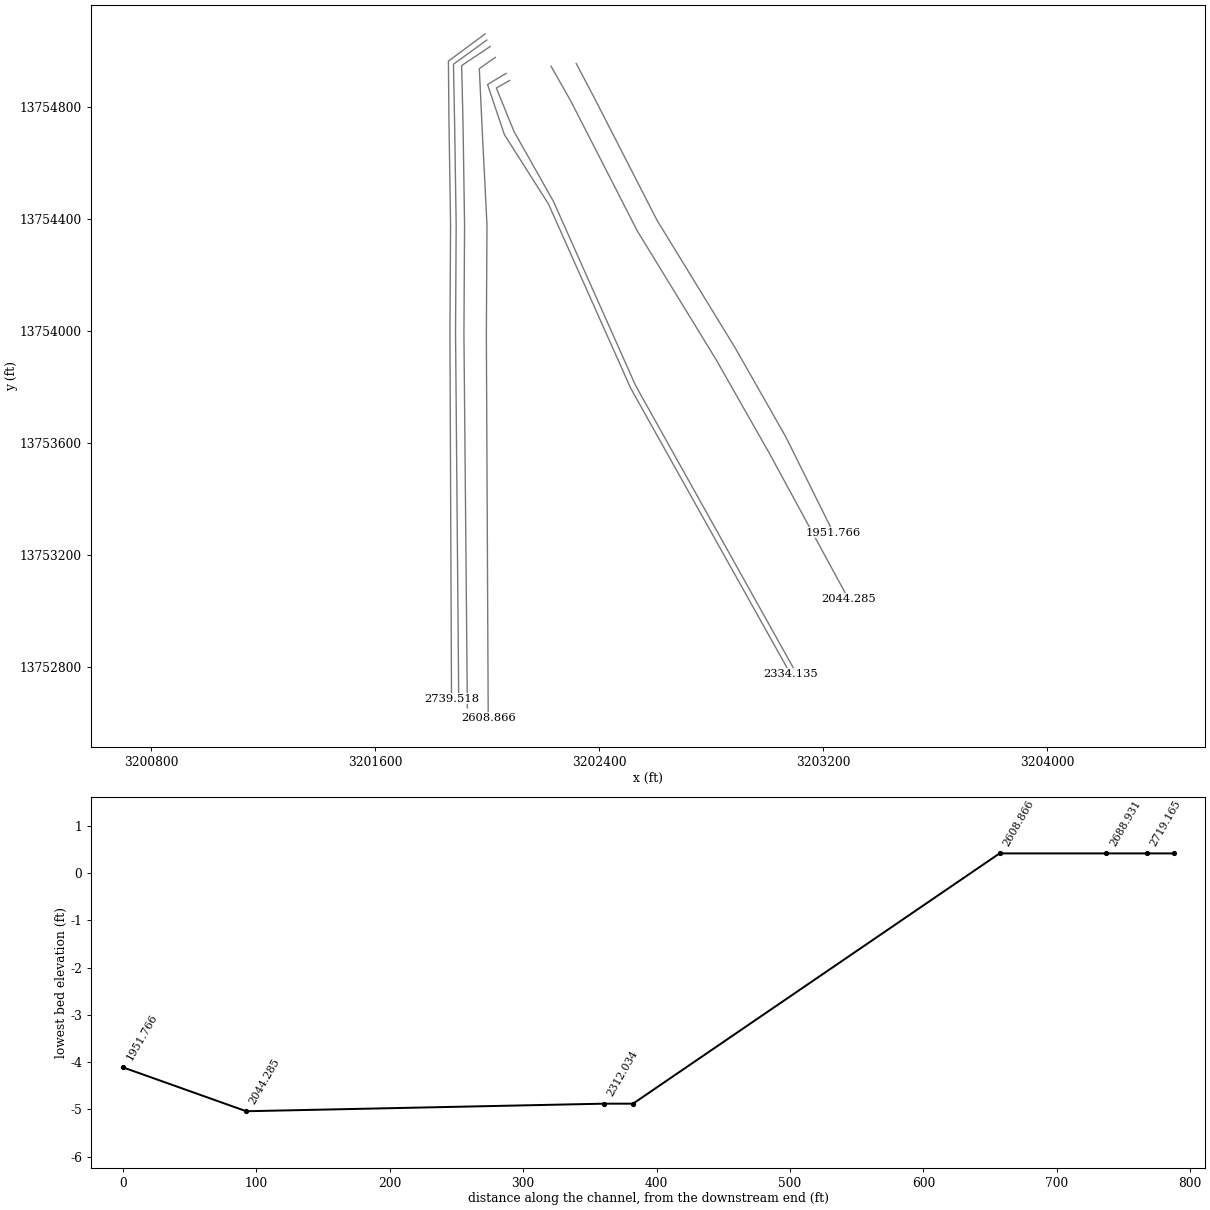
HEC-RAS study A111_00_00.prj: A111-00-00

--- A111_00_00.g01 (geometry) --- (continued)

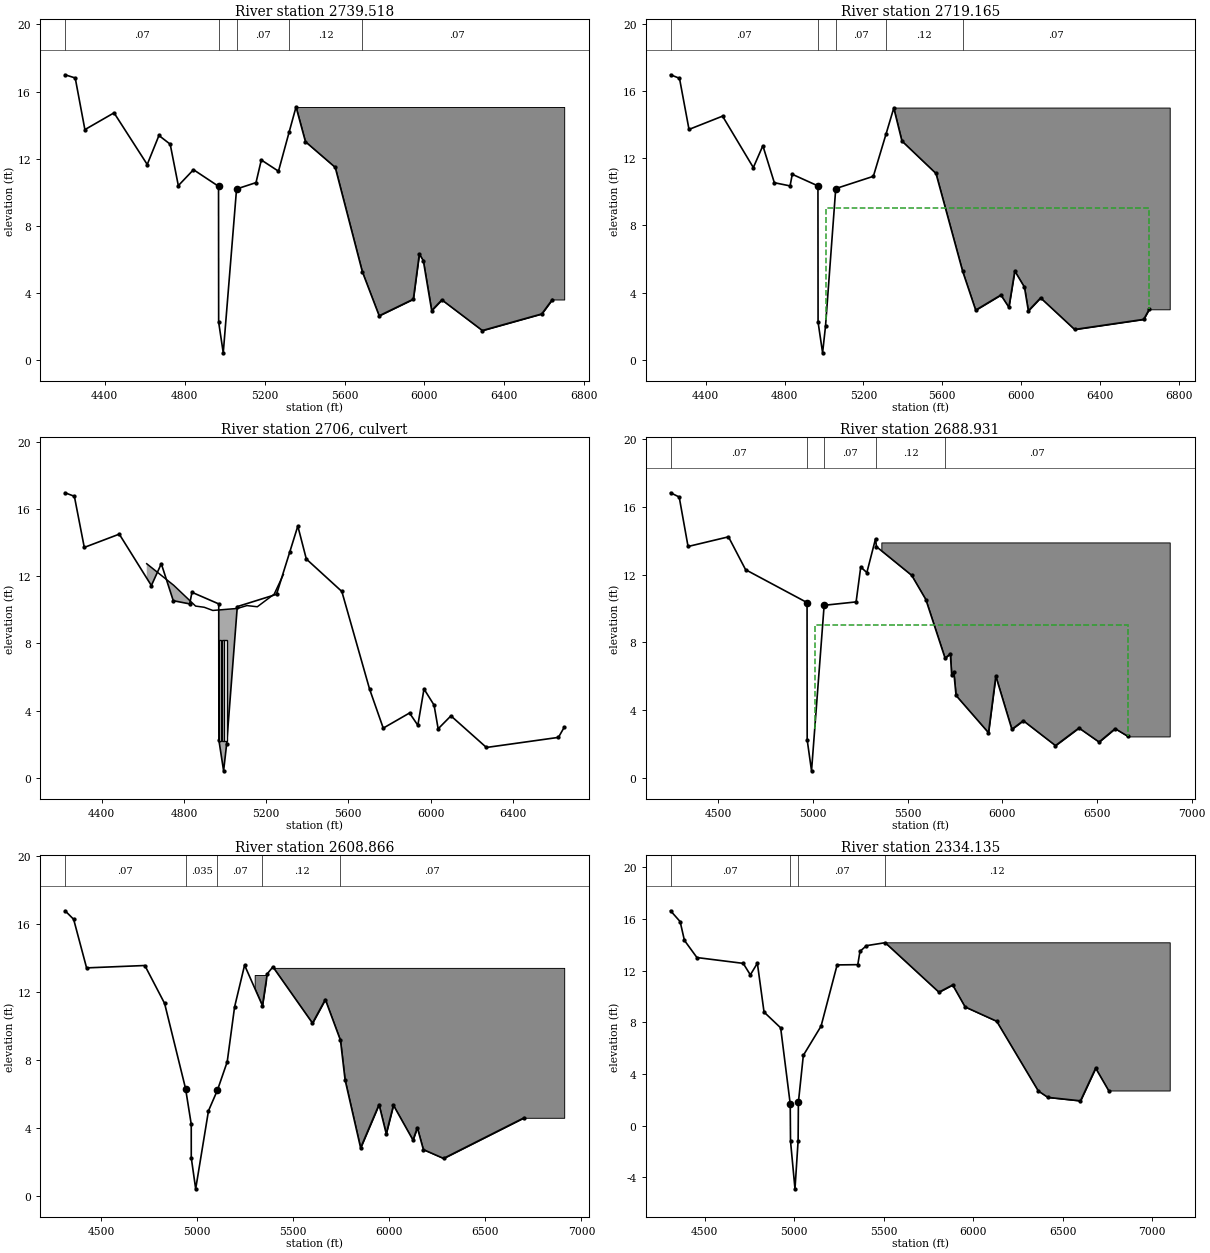
Type RM Length L Ch R = 1 ,2739.518,23.67,20.35,20.76
XS GIS Cut Line= 6
     3201992.933    13755060.691     3201861.982    13754963.585
     3201864.059    13754746.339     3201869.672    13754378.147
     3201867.422    13753987.315     3201873.051    13752687.502
#Sta/Elev= 30
 4201.17      17 4252.03   16.81 4300.44   13.73 4446.35   14.73  4612.5   11.65
 4671.12   13.38 4727.42   12.86 4768.14   10.39 4844.04   11.34 4969.42   10.35
 4970.06    2.25 4993.03     .42 5059.64   10.19 5157.02   10.57  5183.5   11.92
 5269.47   11.25 5323.19    13.6 5357.37   15.08 5404.47   13.01 5553.51   11.48
 5689.07    5.26 5773.47    2.63 5944.47    3.62 5974.47    6.31 5994.42    5.92
 6036.31    2.94  6087.2    3.58 6290.09    1.75 6587.26    2.74 6640.35     3.6
#Mann= 5 ,-1 , 0
 4201.17     .07       0 4969.42    .035       0 5059.64     .07       0
 5323.19     .12       0 5689.07     .07       0
#Block Obstruct= 2 ,-1
 5340.19 5369.34    13.8 5357.41 6699.72   15.08
Bank Sta=4969.42,5059.64
XS Rating Curve= 0
Exp/Cntr=.5,.3

Type RM Length L Ch R = 1 ,2719.165,35.56,30.24,30.82
XS GIS Cut Line= 6
     3201999.002    13755038.844     3201880.059    13754952.672
     3201884.135    13754741.495     3201889.673    13754378.257
     3201887.468    13753994.463     3201898.935    13752671.325
#Sta/Elev= 30
 4221.71   16.96 4266.98   16.75 4315.25   13.71 4485.44    14.5  4641.6   11.44
 4689.91   12.74 4748.14   10.54 4827.95   10.35 4839.17   11.04 4969.42   10.35
 4970.06    2.25 4993.03     .42  5007.9    2.02 5059.64   10.19 5250.53   10.92
 5314.47   13.42 5354.11   14.98 5395.47   13.02 5568.24   11.09 5703.01    5.29
 5769.67    2.96 5897.55    3.86    5938    3.13    5968    5.29 6016.94    4.33
  6036.8    2.92    6099    3.69 6271.65    1.81 6622.01    2.41 6650.07    3.01
#Mann= 5 ,-1 , 0
 4221.71     .07       0 4969.42    .035       0 5059.64     .07       0
 5314.47     .12       0 5703.01     .07       0
#XS Ineff= 2 , 0
       0    4967    8.98    5010       0    9.01
Permanent Ineff=
       F       F
#Block Obstruct= 1 ,-1
 5350.51 6754.08   15.01
Bank Sta=4969.42,5059.64
XS Rating Curve= 0
Exp/Cntr=.5,.3

Type RM Length L Ch R = 2 ,2706    ,,,
BEGIN DESCRIPTION:
FOREST PARK CEMETARY RD
END DESCRIPTION:
Bridge Culvert--1,0,-1,-1, 0
Deck Dist Width WeirC Skew NumUp NumDn MinLoCord MaxHiCord MaxSubmerge Is_Ogee
3,24,2.6,0, 10, 10, , , .95, 0, 0,0,,
    4619    4750 4856.77 4898.74  4940.6 5059.92 5106.51    5157    5239    5284
   12.74   11.46   10.22   10.15    9.96   10.08   10.25   10.18   10.93    12.1
                                                                                
    4619    4750 4856.77 4898.74  4940.6 5059.92 5106.51    5157    5239    5284
   12.74   11.46   10.22   10.15    9.96   10.08   10.25   10.18   10.93    12.1
                                                                                
Multiple Barrel Culv=2,6,12,24,.012,.5,1,8,1,2.19,2.17, 3,Culvert #1  , 0 ,3
  4976.5  4976.5    4989    4989  5001.5  5001.5
Culvert Bottom n=.012
BC Design=,, 0 ,, 0 ,,,,,,
BC HTab HWMax=16.96

Type RM Length L Ch R = 1 ,2688.931,82.41,80.06,82.3
XS GIS Cut Line= 6
     3202011.139    13755015.784     3201909.188    13754947.817
     3201914.065    13754746.362     3201919.674    13754378.422
     3201917.423    13753987.338     3201929.672    13752655.147
#Sta/Elev= 30
 4248.82   16.83 4294.38   16.58 4341.14   13.66 4554.49   14.23    4645   12.29
 4969.42   10.35 4970.06    2.25 4993.03     .42 5059.64   10.19 5228.37   10.39
 5252.79   12.45 5285.11   12.12 5331.02   14.12 5335.73   13.65 5521.64   11.96
 5596.47   10.53 5698.04    7.07 5725.92    7.33 5732.73     6.1 5744.38    6.23
 5755.92    4.87 5927.33    2.67 5965.93    6.01 6050.66    2.87 6111.05    3.38
 6280.94    1.91 6404.95    2.95 6511.12    2.12 6595.96    2.91 6664.18    2.45
#Mann= 5 ,-1 , 0
 4248.82     .07       0 4969.42    .035       0 5059.64     .07       0
 5335.73     .12       0 5698.04     .07       0
#XS Ineff= 2 , 0
       0    4967    8.98    5010       0    9.01
Permanent Ineff=
       F       F
#Block Obstruct= 1 ,-1
 5361.67 6884.12    13.9
Bank Sta=4969.42,5059.64
XS Rating Curve= 0
Exp/Cntr=.5,.3

Type RM Length L Ch R = 1 ,2608.866,126.22,274.73,452.56
XS GIS Cut Line= 6
     3202029.344    13754976.946     3201972.301    13754936.894
      3201982.01    13754730.565     3201999.677    13754378.862
     3201997.424    13753987.305     3202004.088    13752619.557
#Sta/Elev= 30
 4313.53   16.78 4358.14   16.28 4425.53   13.42 4728.53   13.56 4831.35   11.33
 4940.36    6.32 4969.94    4.22 4970.06    2.25 4993.03     .42 5059.64    5.01
 5106.33    6.23 5157.02    7.89 5195.41   11.12 5247.43   13.58 5340.25    11.2
 5365.36   13.07  5394.8   13.48 5600.66   10.17 5667.43   11.56 5746.17    9.16
 5770.06    6.84 5850.98    2.83 5946.88    5.38 5984.29    3.66  6021.7    5.34
 6123.45    3.29 6145.98    4.02 6177.44    2.73 6282.44    2.21 6701.26     4.6
#Mann= 5 ,-1 , 0
 4313.53     .07       0 4940.36    .035       0 5106.33     .07       0
 5340.25     .12       0 5746.17     .07       0
#Block Obstruct= 2 ,-1
 5403.52 6910.13   13.42    5300    5360      13
Bank Sta=4940.36,5106.33
XS Rating Curve= 0
Exp/Cntr=.3,.1

Type RM Length L Ch R = 1 ,2334.135,38.44,22.1,21.39
XS GIS Cut Line= 6
     3202068.183    13754919.902     3202001.685    13754880.333
      3202061.87     13754701.28     3202219.204    13754453.596
     3202512.719    13753795.948     3203082.476     13752777.18
#Sta/Elev= 30
 4308.55   16.64 4362.04    15.8 4385.93   14.35 4455.88   13.02 4714.51   12.57
  4754.3   11.68 4793.61   12.58 4830.86     8.8 4923.72    7.58 4977.19    1.69
 4978.83   -1.19 5003.78   -4.88 5021.33   -1.15 5022.81    1.81 5050.42    5.45
 5149.48    7.71 5239.27   12.45 5354.73   12.47 5367.02    13.5 5403.32   13.94
 5507.89   14.17 5808.08   10.34 5884.78    10.9 5954.32     9.2  6130.8    8.09
 6363.03     2.7 6416.73     2.2 6599.13    1.93 6683.89    4.46 6756.18    2.73
#Mann= 4 ,-1 , 0
 4308.55     .07       0 4977.19    .035       0 5022.81     .07       0
 5507.89     .12       0
#Block Obstruct= 1 ,-1
 5501.32  7097.8    14.2
Bank Sta=4977.19,5022.81
XS Rating Curve= 0
Exp/Cntr=.5,.3

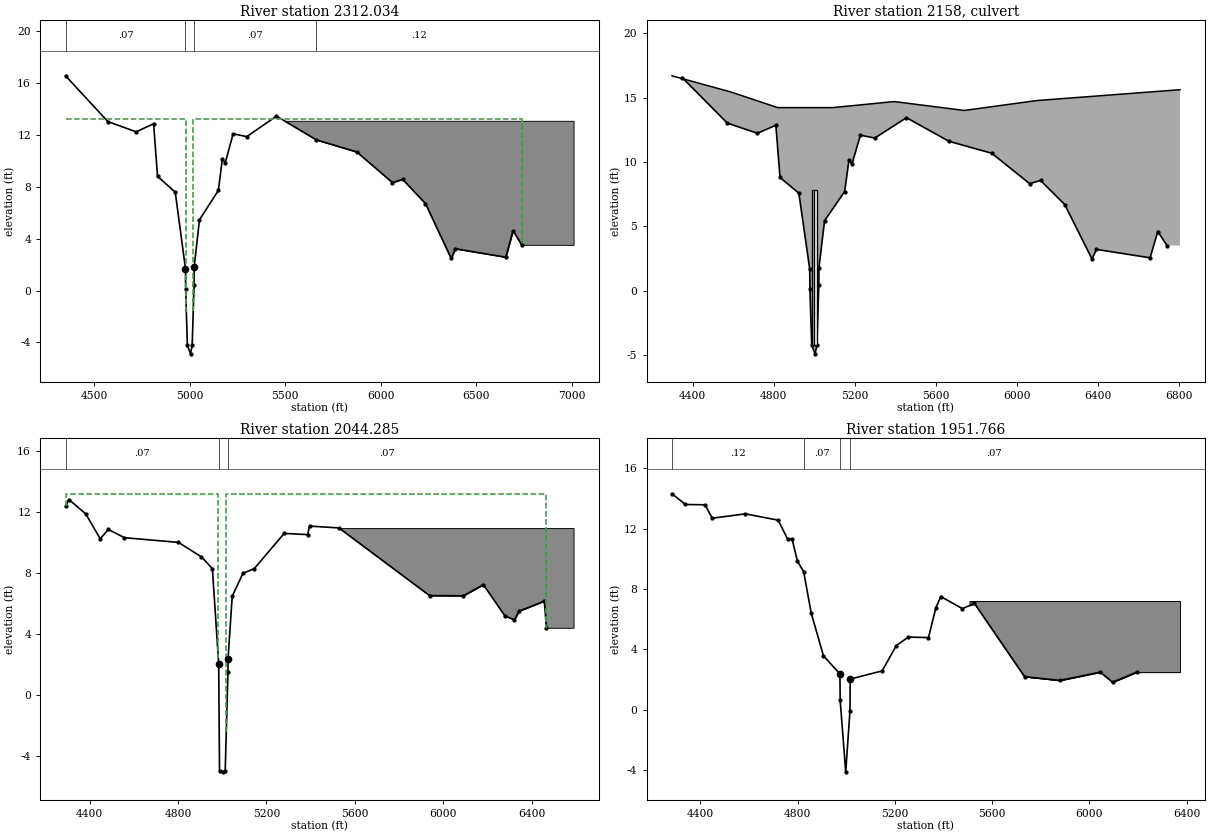
Type RM Length L Ch R = 1 ,2312.034,268.9,267.75,310.81
XS GIS Cut Line= 6
      3202080.32    13754894.414     3202032.986    13754867.713
     3202096.174    13754712.402     3202237.477    13754461.909
     3202530.457    13753805.229     3203096.755    13752791.459
#Sta/Elev= 30
 4348.62   16.55 4570.64   13.02    4719   12.23 4810.12   12.85 4830.86     8.8
 4923.72    7.58 4977.19    1.69 4978.13     .14 4987.07   -4.22 5003.78   -4.88
 5012.33   -4.22 5022.17     .43 5022.81    1.81 5050.42    5.45 5149.48    7.71
 5170.38   10.13 5185.73    9.85 5226.98   12.08  5298.1   11.86 5454.11   13.44
 5663.34   11.61 5874.88   10.68 6061.63    8.32  6115.1    8.57 6234.63     6.7
 6369.26    2.47 6391.09    3.22 6655.56    2.57 6693.34    4.61 6739.01    3.52
#Mann= 4 ,-1 , 0
 4348.62     .07       0 4977.19    .035       0 5022.81     .07       0
 5663.34     .12       0
#XS Ineff= 2 , 0
       0    4982    13.2    5018       0    13.2
Permanent Ineff=
       F       F
#Block Obstruct= 1 ,-1
 5493.39 7010.57   13.08
Bank Sta=4977.19,5022.81
XS Rating Curve= 0
Exp/Cntr=.5,.3

Type RM Length L Ch R = 2 ,2158    ,,,
BEGIN DESCRIPTION:
I-45
END DESCRIPTION:
Bridge Culvert--1,0,-1,-1, 0
Deck Dist Width WeirC Skew NumUp NumDn MinLoCord MaxHiCord MaxSubmerge Is_Ogee
5,250,2.6,0, 8, 8, , , .95, 0, 0,0,,
    4298    4589    4819    5090    5394    5739    6098    6803
   16.69   15.43   14.22   14.22   14.69      14   14.77   15.61
                                                                
    4298    4589    4819    5090    5394    5739    6098    6503
   16.69   15.43   14.22   14.22   14.69      14   14.77   15.61
                                                                
Multiple Barrel Culv=2,12,12,265,.012,.5,1,10,1,-4.19,-4.97, 2,Culvert #1  , 0 ,1
  4993.5  4993.5  5006.5  5006.5
Culvert Bottom n=.012
BC Design=,, 0 ,, 0 ,,,,,,
BC HTab HWMax=16.55

Type RM Length L Ch R = 1 ,2044.285,95.02,92.52,89.96
XS GIS Cut Line= 6
     3202228.391     13754945.39      3202298.38    13754822.006
     3202536.895    13754356.438     3202816.703    13753899.522
     3203007.512    13753564.067     3203289.522    13753044.912
#Sta/Elev= 30
 4290.15   12.38  4305.8   12.82 4381.82   11.88 4447.32   10.25 4484.33   10.86
 4556.72   10.32 4801.66   10.01 4905.73    9.06 4955.14    8.29 4983.72    2.04
 4987.44   -4.98    5002   -5.04 5013.14   -4.98 5025.59    1.49 5026.04    2.38
 5044.86    6.47 5093.75    7.99 5144.17    8.28 5280.01    10.6 5386.44   10.52
 5394.94   11.08 5528.11   10.96 5938.65    6.52 6091.44    6.51 6181.87    7.24
 6279.41    5.19 6322.53    4.93 6343.23     5.5    6458    6.16 6467.63    4.41
#Mann= 3 ,-1 , 0
 4290.15     .07       0 4983.72    .035       0 5026.04     .07       0
#XS Ineff= 2 , 0
       0    4982    13.2    5018       0    13.2
Permanent Ineff=
       F       F
#Block Obstruct= 1 ,-1
 5528.63 6590.31   10.95
Bank Sta=4983.72,5026.04
XS Rating Curve= 0
Exp/Cntr=.5,.3

Type RM Length L Ch R = 1 ,1951.766,192.59,1951.77,112.51
XS GIS Cut Line= 6
     3202318.205    13754955.099     3202382.318     13754833.62
     3202606.752    13754395.536     3202885.592    13753940.216
     3203066.465    13753622.229     3203235.976    13753280.517
#Sta/Elev= 30
 4283.46   14.32 4338.87   13.61 4419.14   13.59 4449.19    12.7 4585.42   12.99
 4720.11   12.57 4759.75   11.29 4777.15   11.33    4799    9.87    4825    9.15
 4855.83    6.42 4906.25    3.58 4973.96    2.38 4974.95     .64 4997.79   -4.11
 5015.22    -.09 5016.28    2.04 5147.46    2.58 5205.92    4.26 5255.02    4.82
 5338.15    4.79 5367.96    6.73 5388.61    7.51 5477.15    6.71 5527.11    7.05
 5733.01     2.2 5878.39    1.95 6044.61     2.5 6094.87    1.83 6194.24     2.5
#Mann= 4 ,-1 , 0
 4283.46     .12       0    4825     .07       0 4973.96    .035       0
 5016.28     .07       0
#Block Obstruct= 2 ,-1
 5506.61 6367.84    7.21 5515.42 6372.25    7.21
Bank Sta=4973.96,5016.28
XS Rating Curve= 0
Exp/Cntr=.3,.1

Chan Stop Cuts=-1

--- A111_00_00.g02 (geometry) ---

Geom Title=A111-00-00 June 2007 (Floodway)
Version=Version 3.0.1  Mar 2001

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
River Reach=A111-00-00,A111-00-00_0020

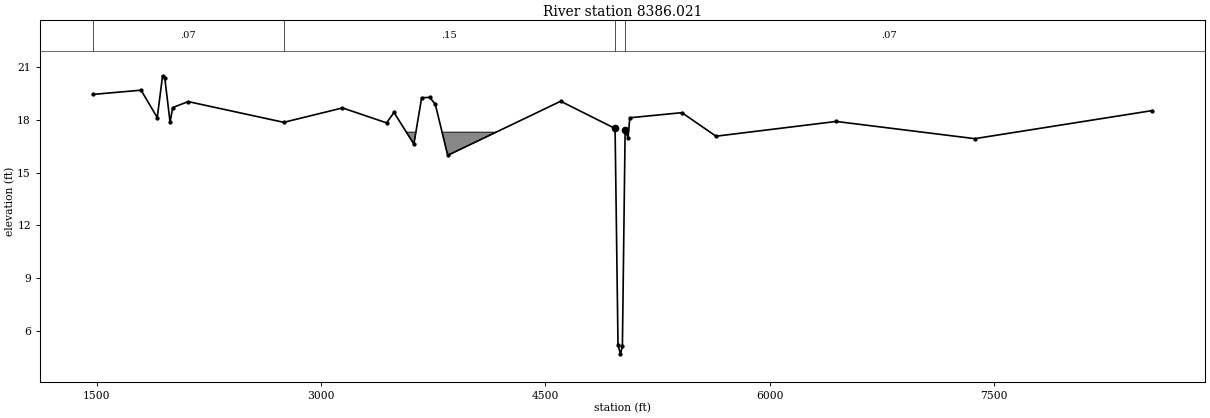
Type RM Length L Ch R = 1 ,8386.021,191.78,881.36,731.88
XS GIS Cut Line= 6
     3201411.915    13760445.259     3198794.184    13758273.637
     3198725.747    13758216.883     3198674.989     13758172.64
     3198602.869    13758113.346      3195908.42    13755984.469
#Sta/Elev= 30
  1475.3   19.45 1796.15   19.69  1904.6   18.13 1940.07   20.51 1954.61   20.41
 1990.27   17.87 2007.99    18.7 2111.51   19.04 2750.57   17.86 3143.34   18.68
 3438.11   17.83 3487.99   18.42 3620.73   16.62 3672.65   19.26 3726.66   19.28
 3763.97   18.89 3847.09   15.98 4602.48   19.06 4966.33   17.51 4985.99    5.17
 5002.35    4.68 5015.28    5.11 5033.67   17.45 5052.97   16.98  5064.8   18.12
 5413.09   18.41 5641.35   17.07  6445.1   17.91 7371.85   16.93 8560.12   18.53
#Mann= 4 ,-1 , 0
  1475.3     .07       0 2750.57     .15       0 4966.33    .015       0
 5033.67     .07       0
#Block Obstruct= 1 ,-1
    3560    4230    17.3
Bank Sta=4966.33,5033.67
XS Rating Curve= 0
Exp/Cntr=.5,.1